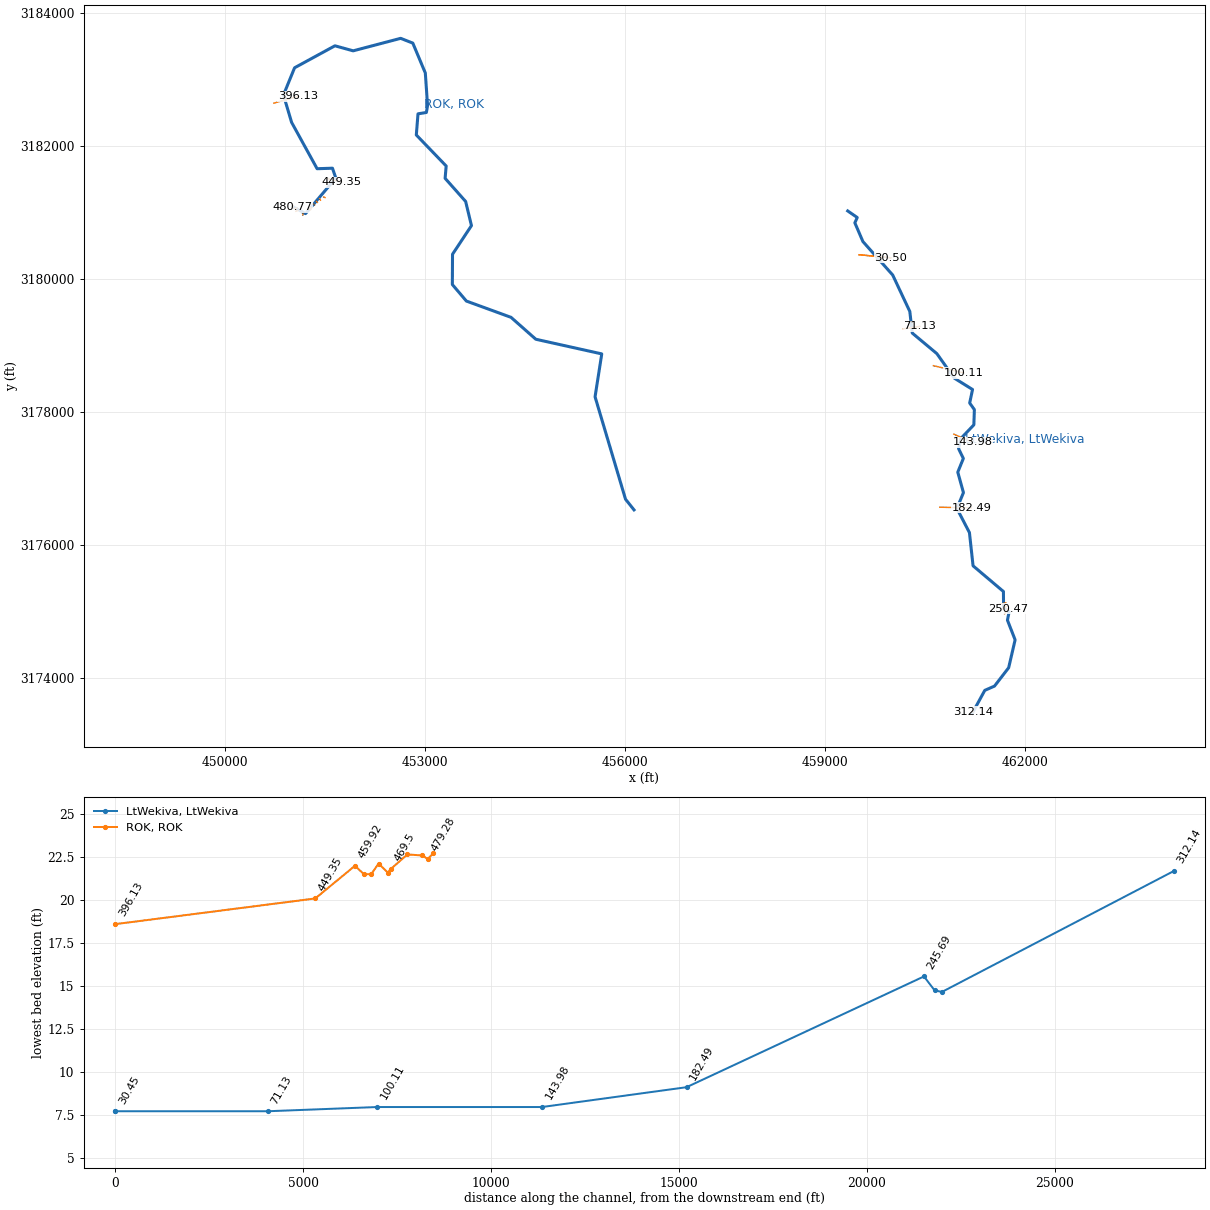
HEC-RAS study wekiva_ras.prj: wekiva_ras

--- wekiva_ras.u01 (unsteady flow) ---

Flow Title=unsteady_BC_2008
Program Version=5.03
Use Restart= 0
Boundary Location=LtWekiva        ,LtWekiva        ,312.14  ,        ,                ,                ,                ,
Interval=1DAY
Flow Hydrograph= 153
     2.4    2.18    1.91    1.71    1.54    1.47    1.28    1.12    1.93    9.57
    8.92    9.59    14.7    18.6    19.5    44.3    36.3    41.3    39.7    38.9
      37    31.9    27.1    22.8    19.3    21.1    21.2    20.5    19.6    18.2
    15.8    13.8    13.3    19.2    14.5    13.1      12    15.5    12.4    11.5
    15.4    21.1    35.9    62.6     109     143     197     207     187     156
     122    94.2     105     111     116     101    92.8    97.8     124     114
     100    93.9    75.7    60.5      50    48.8    33.9    28.2    24.4    23.8
    22.1    20.7    22.9    20.5      20      20    18.3    16.3    19.1    26.2
    55.9     264     506     536     522     494     444     368     313     270
     245     244     232     222     183     158     141     119     110     110
     112    91.8    92.2     121     132     128     145     165     155     142
     123    96.9    76.2    68.3    72.1    63.2      55      54    49.2    44.5
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Use DSS=False
Use Fixed Start Time=True
Fixed Start Date/Time=01JUN2008,2400
Is Critical Boundary=False
Boundary Location=ROK             ,ROK             ,480.77  ,        ,                ,                ,                ,
Interval=1DAY
Flow Hydrograph= 153
    47.5    47.3    47.4    47.3      47    46.6    46.3    45.8    45.6    45.6
    45.8    45.6    45.7    45.9    46.5    46.7    46.9    47.1    47.4    47.3
    47.4    47.2    46.9    46.9    46.9      47    47.5    47.6    47.7    47.6
    47.5    47.5    47.5    47.6    47.8    47.8    47.6      48      49      48
    47.8      48      48    48.1    50.3    49.2    49.3    49.2    49.2    49.3
    49.3    49.4    49.5    49.4    49.2    49.4    49.6    49.5    49.5    49.8
    50.1    50.5    50.3    50.5    50.3    50.3    50.3    49.9      50      50
    49.7    49.5    49.7    49.9    50.2    50.3    50.1    49.9    49.9    49.9
    50.5    57.9    68.8    72.3    69.2      63    60.1    58.6    57.7    57.7
    58.5    58.5    58.1    57.8    58.2    58.2    58.3    58.3    58.2    58.2
    58.1    58.5    58.7    58.9    59.2    58.7    58.8    58.8    58.8    58.9
    58.8    58.9    58.8    58.5    58.6    58.6    58.7    58.8    58.8    58.6
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Use DSS=False
Use Fixed Start Time=True
Fixed Start Date/Time=01JUN2008,2400
Is Critical Boundary=False
Boundary Location=wekiva          ,wek_run         ,793.32  ,        ,                ,                ,                ,
Interval=1DAY
Flow Hydrograph= 153
    50.6    50.4    50.5    50.5    50.1      50    49.9    49.7    49.7    50.3
    50.9    50.9    51.2    51.4    51.3    51.7    52.3    52.1    52.2    52.3
    52.3    52.7    52.8    52.9    52.7    52.9    53.2    53.5    53.4    53.6
    53.7    53.7    53.6    53.6    53.4    53.4    53.4    53.4    53.8    53.5
    53.5    53.6    53.6    53.8    53.9    54.5      55    55.5    55.4    55.4
    55.3    55.2    55.2    55.5    55.3    55.5    55.6    55.7    55.9    56.1
    56.3    56.5    56.5    56.2      56    55.8    55.6    55.3    55.4    55.4
    55.2    55.1    55.1    55.4    55.3    55.6    55.5    55.5    55.5    56.3
    56.9      57    56.4      58    65.1    71.6    72.8    73.1    73.3    73.5
    73.3    73.7    73.8    74.1    74.1    73.9    74.2    74.1    73.7    73.6
    73.6    73.6    74.1    74.8    74.9    74.7    74.4    74.5    74.8    74.7
    74.7    74.6    74.3    74.1    74.3    74.4    74.1    74.1    74.2    73.6
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Use DSS=False
Use Fixed Start Time=True
Fixed Start Date/Time=01JUN2008,2400
Is Critical Boundary=False
Boundary Location=wekiva          ,wekiva_riv_down ,0       ,        ,                ,                ,                ,
Interval=1HOUR
Stage Hydrograph= 3672
    -.25    -.26    -.25    -.27    -.28    -.29    -.29    -.25    -.26    -.26
    -.23    -.23    -.22    -.26    -.24    -.24    -.25    -.24    -.21    -.25
    -.31    -.28    -.29    -.31    -.31     -.3    -.31    -.32     -.3    -.31
    -.32    -.32    -.32    -.28    -.29    -.27    -.28    -.29    -.27    -.28
    -.25    -.28    -.29    -.31    -.35    -.31    -.32    -.33     -.3     -.4
    -.38    -.36    -.36    -.34    -.38    -.35    -.34    -.36     -.3    -.32
    -.29    -.29    -.31    -.33    -.34    -.35    -.35    -.37    -.33    -.23
    -.36    -.35    -.35    -.37    -.32    -.35    -.36    -.36    -.36    -.36
    -.36    -.33    -.32    -.32    -.31    -.28     -.3     -.3    -.32    -.22
    -.28    -.35    -.38    -.35    -.35    -.36    -.38    -.36    -.36    -.37
     -.4     -.4    -.41    -.42    -.41    -.39    -.37    -.36    -.35    -.37
    -.34    -.31    -.26    -.27    -.33    -.33    -.36    -.42    -.42    -.44
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Use DSS=False
Use Fixed Start Time=True
Fixed Start Date/Time=01JUN2008,0000
Is Critical Boundary=False
Boundary Location=LtWekiva        ,LtWekiva        ,250.47  ,        ,                ,                ,                ,
Interval=1DAY
Lateral Inflow Hydrograph= 153
   32.37   32.58   32.43   32.23   31.94   32.35   32.08   32.14    32.4   32.87
   33.62   35.32   34.15   34.38   34.08   35.26   36.12   36.56   38.27   37.34
   37.19   37.02   36.71      36   35.91   36.42   36.88   36.49    36.1   36.09
   36.58   36.42   36.91   37.66   37.21   36.83   37.34    37.9   38.45   37.91
   38.22    38.1   37.86    39.1      40   43.17   42.65   43.28   42.03   41.25
   40.65   40.02   40.55   40.62   40.98   39.88   39.92   42.27   42.86   42.58
   43.71    42.9    44.3   42.66   41.04   40.14   39.13   38.71   38.62    38.9
   39.39   40.42   40.02   39.25   40.17   39.85   39.78   40.18   40.65   42.07
    45.9   65.17  152.87   90.14   69.46   66.23   63.33   55.23   50.94   49.22
   48.13   50.33   47.71   46.42   43.99   41.84   41.35   41.04   39.45   40.31
   44.46   43.34   44.72   46.38   47.03   46.73   47.19   45.97   49.97   49.57
   48.71   48.22   48.78   48.89   49.42   50.38   49.55   48.19   49.06   48.85
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Use DSS=False
Use Fixed Start Time=False
Is Critical Boundary=False
Boundary Location=LtWekiva        ,LtWekiva        ,182.49  ,        ,                ,                ,                ,
Interval=1DAY
Lateral Inflow Hydrograph= 153
     .66     .73     .66     .91      .7     .64     .63     .62     .63     .62
     4.3   12.38    3.41    1.72    1.27     .99    2.74    1.36    6.91     2.8
    2.15    2.83    1.86    1.18     .93     .81    1.01     .98     .74     .94
     .81     .75     .71     .67     .64     .62     .62     .63    3.46    1.57
     .72     .66     .67    2.03     5.2   16.19    9.19    9.17    6.26    3.87
    2.55    1.71    1.22   13.71    5.84    3.48     2.6    8.25    4.82    3.56
   14.24   11.59   12.29    8.48    6.32    4.02    2.85    2.05    1.53    1.26
    2.47    7.02    3.71    2.57    6.89    4.37    2.97    2.89    2.24    6.21
   18.79   59.67  356.37  141.98    70.2   47.08   42.52   19.83   12.11    9.72
    7.52   16.57    8.15    6.45    5.44    4.38    3.74    3.72     3.1    2.84
    2.66    2.54    2.93    2.71    2.41    2.33    2.53    2.71    2.37    2.33
    2.32    2.33    2.24    2.18    3.58     7.6    3.93    2.93    2.61    2.42
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Use DSS=False
Use Fixed Start Time=False
Is Critical Boundary=False
Boundary Location=LtWekiva        ,LtWekiva        ,143.98  ,30.50   ,                ,                ,                ,
Interval=1DAY
Uniform Lateral Inflow Hydrograph= 153
    1.38     1.5    1.35     1.8    1.35    1.35    1.34    1.32    1.35    1.32
     6.3   18.47    3.92    2.92     2.2    1.72    4.57    1.73   11.42    4.41
    4.16     5.4    3.39     2.4    1.78    1.56    2.11    1.51    1.43    1.88
    1.39    1.55     1.4    1.39    1.34    1.32    1.32    1.35     6.2    1.34
     1.3    1.29    1.36    4.19    7.76   26.25   19.74   21.69   16.28   11.07
    7.01    4.33    2.81   25.24   14.41    9.55    6.76   17.04   11.75     9.5
   31.14   27.32   30.97    24.8   17.91   12.03    8.09    5.45    3.71    2.81
     4.6    13.1    7.81    6.48   13.99   10.09     7.9    7.07    5.58   13.43
    40.2  152.67  774.71  299.47  150.81  130.33  111.25   59.61   37.24   27.91
   21.29   38.83   22.39   16.83    13.7   11.27     9.2    8.58    7.16     6.3
    5.64    5.22    5.79    5.04    4.82    4.66    5.07    4.95    4.68    4.65
    4.64    4.68    4.48    4.36    6.67   12.16     6.1    5.55    5.03    4.71
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Use DSS=False
Use Fixed Start Time=False
Is Critical Boundary=False
Boundary Location=ROK             ,ROK             ,350.27  ,        ,                ,                ,                ,
Interval=1DAY
Lateral Inflow Hydrograph= 153
     .18     .21     .23      .3      .3     .18     .11     .06     .03     .02
     .79    1.81     2.9    2.15    1.58     1.1    1.07    1.03     1.6    1.87
    1.44    1.37    1.26      .9     .64     .47     .42     .48     .33     .26
      .3     .24      .3     .23     .19     .12     .07     .05      .4     .83
     .56     .36     .25      .4    1.16    2.69    4.18    3.56    3.06    2.18
    1.53    1.05     .75    2.04    2.63    1.87    1.39    1.95    2.11    1.71
    2.08    3.08    3.33     3.1    2.42    1.77    1.33    1.01     .79     .67
      .9    1.75    1.99    1.53    2.09    2.14     1.8    1.61    1.44     1.7
    4.03    6.01    36.1   45.72   43.07   33.44   27.65   23.02   18.93   16.61
   14.87   14.41   13.85   12.65   11.79   10.93   10.17    9.71    9.22    8.59
    8.09    7.68    7.37    7.22    6.84    6.45    6.12    6.08    5.82    5.53
    5.28    5.07    4.85     4.6    4.75    5.63    6.04    5.65    5.28    4.92
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Use DSS=False
Use Fixed Start Time=False
Is Critical Boundary=False
Boundary Location=ROK             ,ROK             ,18.17   ,        ,                ,                ,                ,
Interval=1DAY
Lateral Inflow Hydrograph= 153
    6.44    6.21    6.03    5.98     5.9     5.5    5.13    4.79    4.51    4.34
    6.43    9.64   14.67   14.64   14.06   13.06   12.79   12.63   13.87   15.28
   14.56   14.34   14.03   12.87    11.7   10.65    9.86    9.47    8.64    7.98
    7.67    7.16    6.97    6.53     6.2    5.78    5.38    5.12    5.84    7.39
    7.14    6.78    6.46    6.69    8.78   13.61   20.22   21.38   22.03   20.72
    19.1   17.38   15.78    18.3   20.96   19.72   18.44   19.54   20.46   19.56
   20.37   23.95    25.9   26.58   25.46   23.69   21.92   20.19   18.57   17.18
   16.73   18.37    19.5   18.54   19.96   20.57   19.91   19.28   18.59   18.79
   25.61   33.68  144.02  235.87  230.59  190.49  179.27  166.39  150.18  138.06
  127.94     123  117.27  109.19  102.97   96.19   87.88   79.99   72.42   64.96
   58.77   53.76   49.96   47.53   44.73   42.26   40.29   39.69   38.69   37.76
   36.94   36.25   35.57   34.84   35.11    37.7   39.79   39.12   38.21   37.21
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Use DSS=False
Use Fixed Start Time=False
Is Critical Boundary=False
Boundary Location=ROK             ,ROK             ,350.27  ,215.81  ,                ,                ,                ,
Interval=1DAY
Uniform Lateral Inflow Hydrograph= 153
    3.86    3.78    3.75    3.82    3.77    3.76    3.73     3.7    3.76    3.69
    4.12    5.23    3.83    3.81    3.75    3.73    3.97    3.72    4.43    3.77
    3.81    4.05    3.85    3.75    3.77     3.7     3.8    3.76    3.67    3.66
    3.64     3.8    3.66    3.66    3.57    3.54    3.56    3.62    3.99    3.56
    3.48    3.47    3.58    3.75    4.06     5.5    4.05    4.32    3.91    3.78
    3.73    3.69    3.77    5.28    4.07       4     4.1    4.79    4.22    4.31
    7.17    5.12    5.26    4.93    4.67    4.73    4.71    4.65    4.66    4.76
    4.98    5.51    4.93    5.13    5.71    6.29    5.39    5.44    5.25    6.08
    8.66   29.71  485.16  160.87   59.25   53.69   50.71   38.64   38.17    38.2
   38.12    46.5   39.76   38.83   37.76   36.55   35.54   35.29   33.21   32.61
   32.02   31.32   30.19   30.15   29.11   28.16   27.37   26.87   26.86   26.31
    25.8   25.45   24.47   23.69   24.01   26.05   26.14   25.56   24.76   23.81
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Use DSS=False
Use Fixed Start Time=False
Is Critical Boundary=False
Boundary Location=wekiva          ,wekiva_riv_up   ,711.81  ,579.74  ,                ,                ,                ,
Interval=1DAY
Uniform Lateral Inflow Hydrograph= 153
    1.42    1.49    1.38    1.73    1.38    1.38    1.37    1.35    1.37    1.35
    5.16   15.71     6.1    4.03    2.51     1.6     3.8    1.66   12.27    8.88
    6.65     7.8    6.39    3.75    2.06    1.66    2.07     1.6    1.54    1.88
     1.5    1.61    1.48    1.46     1.4    1.36    1.34    1.35    5.04    1.33
     1.3    1.29    1.35    3.51    6.29   31.62   52.13   51.41    46.1   30.72
   18.36   10.13     5.3   39.29   40.18   25.79   16.18   31.86   32.43   24.25
    46.3      66   77.82   68.93   51.02   33.33   21.15   12.91    7.45    4.41
    5.62   19.57   19.27   13.38   25.45   24.69   18.94   15.05   12.16   20.58
   84.76  212.96 1005.77  505.12  279.61  169.11  135.49   87.23   55.58   40.84
   31.69   45.19   32.99   24.63   19.71      16   12.71   11.32    9.52    8.05
    6.92    6.19    6.38    5.85    5.59    5.39    5.67    5.54    5.38    5.36
    5.38    5.45    5.23    5.11    6.88   11.64    7.32    6.43    5.63    5.29
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Use DSS=False
Use Fixed Start Time=False
Is Critical Boundary=False
Boundary Location=wekiva          ,wekiva_riv_down ,508.92  ,370.65  ,                ,                ,                ,
Interval=1DAY
Uniform Lateral Inflow Hydrograph= 153
     2.8    2.85    2.72    3.09    2.73    2.73     2.7    2.67    2.71    2.66
    6.53   15.81     4.4    3.75    3.22    2.81    5.04    2.84   10.62    5.46
    5.18    6.26    4.74    3.79    3.16    2.84    3.27    2.82    2.75    3.08
    2.71    2.91    2.72    2.71    2.63     2.6     2.6    2.66     6.4    2.63
    2.57    2.56    2.67    4.83    7.59   22.14   17.24   18.59   14.42   10.54
     7.5    5.39    4.15   22.01   13.76    9.83    7.62   15.75    11.7    9.92
   27.28   24.07   26.26   21.24   16.06   11.91    9.03    6.94    5.49    4.72
    6.14   13.22    9.31    8.12   14.29   11.92    9.54    8.79    7.48   13.81
   36.12  127.24  995.41  423.27  209.24  123.21  100.75   53.19   34.71   27.52
   22.57   39.31   24.41   20.15   17.81   15.93   14.53   14.48    12.7   12.26
   11.91   11.55    11.6   11.27   10.73   10.31   10.46   10.28   10.26   10.25
   10.29   10.44   10.03    9.81   11.72   16.36   11.84   11.37   10.73   10.11
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Use DSS=False
Use Fixed Start Time=False
Is Critical Boundary=False
Boundary Location=wekiva          ,wekiva_riv_down ,386.11  ,        ,                ,                ,                ,
Interval=1DAY
Lateral Inflow Hydrograph= 153
   15.22   15.21    15.2   15.19   15.07   15.01   14.94   14.89   14.89   15.13
   15.31   15.38   15.45    15.5   15.46   15.54   15.66   15.67   15.78   15.81
   15.86    15.9   15.91   15.87   15.88   15.91   15.99   16.05   16.05   16.18
   16.21   16.23    16.2   16.21   16.17   16.12   16.09   16.15    16.2   16.16
   16.23   16.39   16.47    16.6   16.71    16.9   17.07   17.21   17.19   17.21
   17.16   17.12   17.13   17.21   17.24    17.3   17.34   17.56   17.66   17.66
   17.63   17.61   17.56   17.46   17.39   17.33   17.29    17.2   17.16    17.2
   17.17   17.16   17.14   17.11   17.06   17.12   17.13   17.15   17.18   17.38
   17.73   18.46   19.37   19.91   20.21   20.32   20.42   20.37    20.3   20.27
   20.32   20.58    20.6   20.59   20.52   20.44   20.41   20.33   20.24   20.18
   20.16   20.16   20.34   20.58   20.56   20.48   20.41   20.56   20.54   20.45
    20.4   20.36   20.25   20.21    20.3    20.3   20.23   20.21   20.14   20.03
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Use DSS=False
Use Fixed Start Time=False
Is Critical Boundary=False
Boundary Location=wekiva          ,wekiva_riv_down ,370.65  ,        ,                ,                ,                ,
Interval=1DAY
Lateral Inflow Hydrograph= 153
     .32     .31      .3      .3     .29     .27     .26     .24     .23     .21
     .28     .39     .55     .53     .51     .49      .5      .5     .56     .62
      .6     .61     .62     .59     .56     .54     .52     .52     .49     .47
     .46     .44     .43     .42      .4     .38     .36     .34     .36      .4
     .38     .36     .34     .35     .42     .58      .8     .82     .84     .81
     .77     .74      .7     .82     .92     .88     .85     .91     .95     .93
     .98    1.12    1.19    1.22    1.19    1.15     1.1    1.06    1.02     .99
     .99    1.06     1.1    1.06    1.12    1.14    1.12     1.1    1.09     1.1
    1.36    1.63    8.21   13.08   15.04   14.26   13.76   13.03   11.89   10.95
   10.12    9.66    9.19     8.5    7.93    7.38    6.88    6.49    6.12    5.72
    5.39    5.09    4.85    4.67    4.44    4.23    4.03    3.94     3.8    3.64
     3.5    3.39    3.27    3.16    3.16    3.41    3.53    3.41    3.28    3.16
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Use DSS=False
Use Fixed Start Time=False
Is Critical Boundary=False
Boundary Location=wekiva          ,wekiva_riv_down ,344.64  ,322.22  ,                ,                ,                ,
Interval=1DAY
Uniform Lateral Inflow Hydrograph= 153
     .76     .78     .74     .84     .74     .74     .74     .73     .74     .72
    1.78    4.31     1.2    1.02     .88     .77    1.37     .77    2.89    1.49
    1.41    1.71    1.29    1.03     .86     .77     .89     .77     .75     .84
     .74     .79     .74     .74     .72     .71     .71     .73    1.74     .72
      .7      .7     .73    1.31    2.07    6.03    4.69    5.06    3.92    2.87
    2.04    1.47    1.13    5.99    3.75    2.68    2.08    4.29    3.19     2.7
    7.43    6.55    7.15    5.78    4.37    3.24    2.46    1.89    1.49    1.29
    1.67     3.6    2.54    2.21    3.89    3.24     2.6    2.39    2.04    3.76
    9.84   34.64  271.02  115.24   56.97   33.55   27.43   14.48    9.45    7.49
    6.14    10.7    6.65    5.49    4.85    4.34    3.96    3.94    3.46    3.34
    3.24    3.15    3.16    3.07    2.92    2.81    2.85     2.8    2.79    2.79
     2.8    2.84    2.73    2.67    3.19    4.46    3.22    3.09    2.92    2.75
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Use DSS=False
Use Fixed Start Time=False
Is Critical Boundary=False
Boundary Location=wekiva          ,wekiva_riv_down ,143.23  ,        ,                ,                ,                ,
Interval=1DAY
Lateral Inflow Hydrograph= 153
     .27     .24     .22     .21     .21     .17     .13      .1     .08     .06
     .38     .95    1.78    1.65    1.52    1.38     1.4    1.43    1.77     2.1
    1.97    1.99    1.98    1.81    1.65    1.51     1.4    1.35    1.22    1.11
    1.06     .96     .89      .8     .72     .64     .56     .49      .6     .82
     .72     .64     .56     .58     .92    1.88     3.2    3.31    3.42    3.16
     2.9    2.65    2.43    3.19    3.82    3.53    3.27    3.63    3.87    3.67
    3.98    4.98    5.45    5.59    5.31    4.94    4.59    4.27    3.96    3.69
    3.62    4.05    4.29    4.01    4.37    4.48    4.24    4.06    3.88    3.99
    7.15   11.22   63.82  128.41  157.06  145.47  135.02  122.59  101.68   85.06
   71.23   64.39   58.46   49.98   47.42   45.22   43.09   41.24   39.43   37.51
    35.7      34   32.46   31.16   29.66    28.2   26.84   25.81   24.63   23.42
   22.27   21.19   20.15   19.15   18.49   18.53   18.31   17.44   16.59   15.76
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Use DSS=False
Use Fixed Start Time=False
Is Critical Boundary=False
Boundary Location=wekiva          ,wekiva_riv_down ,276.66  ,25.630* ,                ,                ,                ,
Interval=1DAY
Uniform Lateral Inflow Hydrograph= 153
    1.21    1.19    1.18     1.2    1.18    1.18    1.17    1.16    1.17    1.15
    1.34    2.34    2.17    1.72    1.39     1.2    1.31    1.21    2.45    2.69
    2.12    2.25    2.18    1.63     1.3    1.21    1.24    1.22    1.19    1.19
    1.17    1.22    1.17    1.16    1.13    1.11    1.11    1.13    1.31    1.12
     1.1    1.09    1.14    1.22    1.39    5.28   10.61    9.47    8.45    5.76
    3.81    2.55    1.82    6.43    7.73    5.22    3.62    5.63     6.3    4.92
    8.26    11.2   12.57   11.23    8.42    5.92    4.28    3.16    2.39    1.97
    2.04    4.07    4.71    3.63    5.41     6.1    4.76    4.02    3.52    4.48
   15.85   43.71  383.45  135.66   46.33   27.46   21.83   14.26   13.05   10.75
    9.43   13.86   10.27     8.6    7.63    6.88    6.31    6.22     5.5     5.3
    5.15    5.02    4.79    4.93    4.73    4.64     4.6    4.54    4.66    4.67
    4.69    4.75    4.57    4.46    4.64     5.3     5.2    4.95     4.7     4.5
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Use DSS=False
Use Fixed Start Time=False
Is Critical Boundary=False
Boundary Location=wekiva          ,wekiva_riv_down ,25.630* ,        ,                ,                ,                ,
Interval=1DAY
Lateral Inflow Hydrograph= 153
   45.38   44.72   44.18   44.16   44.18   43.61   42.99   42.33   41.78   42.24
   47.75   55.46   70.57   68.15   65.19   62.15   64.68   68.41   77.62   87.19
   85.06   84.89   83.73   78.81   74.17   74.26   77.53   82.05   86.96   89.89
  101.29  111.22   111.4  104.05   97.53   91.74   86.19   81.57   82.69   85.72
   80.34   77.32   75.44   76.85   85.89   106.7  142.81  145.52  145.03  132.33
  118.73  106.08   97.26  111.97  134.19   128.6  122.04  127.19  134.21  126.62
  127.17  152.72   161.5  158.08  141.09  121.86  105.35   92.26   82.49    76.6
   74.51   80.24   84.32   79.41   83.67   85.32    81.3   78.42   75.98   78.29
  122.61     183  861.56 1245.61 1192.11 1012.34  873.99  732.39  577.23  465.74
  392.71  349.76  316.75  282.01  256.21  233.04  211.74  194.19  178.49  164.07
  146.85  130.04  122.66  124.73  127.43   127.5  125.77  126.17  125.58  127.94
   130.1  128.47  125.47  121.78  121.15  127.85  129.63   121.1  113.82  107.96
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Use DSS=False
Use Fixed Start Time=False
Is Critical Boundary=False
Boundary Location=wekiva          ,wekiva_riv_up   ,747.19  ,        ,                ,                ,                ,
Interval=1DAY
Lateral Inflow Hydrograph= 153
     .79     .83     .76     .96     .76     .76     .75     .75     .76     .74
    2.95    7.64     .86     .85     .83     .82    2.08     .83    4.38     .88
    1.25    1.79      .9     .86     .86     .84    1.11     .85     .82    1.03
     .81     .88     .81      .8     .78     .77     .77     .78    2.91     .79
     .77     .76     .79    2.03    3.59    8.34     1.5    2.62       1     .96
     .94     .92     .94       7    1.04    1.01    1.23    4.21    1.07    1.33
    5.81    2.97    3.23    1.56    1.19     1.2    1.19    1.17    1.17     1.2
       2    4.28    1.23    1.58    3.63    1.57    1.36    1.62    1.31    4.31
    7.22    17.8  150.73   49.21   13.49   12.52   11.27    4.56    4.51    5.08
    4.61    9.48     4.9    4.79    4.77    4.65    4.62    4.85    4.39    4.42
    4.45    4.43     4.7    4.37    4.23    4.14     4.3    4.21    4.08    4.05
    4.03    4.04     3.9    3.81    4.82    6.98    4.13    4.06    3.95    3.82
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Use DSS=False
Use Fixed Start Time=False
Is Critical Boundary=False

--- wekiva_ras.g01 (geometry) ---

Geom Title=wekiva_ras_2018_ft_4
Program Version=5.03

Junct Name=Junc_LtWek
Junct Desc=, 0 , 0 ,-1 ,0
Up River,Reach=LtWekiva        ,LtWekiva
Up River,Reach=wekiva          ,wekiva_riv_up
Dn River,Reach=wekiva          ,wekiva_riv_down
Junc L&A=0,0
Junc L&A=0,0

Junct Name=Junc_Rok
Junct Desc=, 0 , 0 ,-1 ,0
Up River,Reach=ROK             ,ROK
Up River,Reach=wekiva          ,wek_run
Dn River,Reach=wekiva          ,wekiva_riv_up
Junc L&A=0,0
Junc L&A=0,0

River Reach=LtWekiva        ,LtWekiva
Reach XY= 30
 461210.722404883173468.02397002461399.0711048793173813.90187002
 461544.923404883173878.29017002 461756.951404883174153.97287002
 461853.759004883174572.90287002461738.7675048793174868.43627002
 461763.894404883174995.06247002 461680.720004883175051.39747002
461678.4189048793175299.57177002461223.1042048793175685.60017002
 461168.883004883176184.43507002 460980.871804883176547.67637002
 461078.951904883176785.36127002460994.0494048793177093.09957002
 461077.364904883177299.00777002461005.9516048793177446.19837002
 461043.245204883177602.24967002 461235.178304883177804.45507002
 461242.721704883178033.17637002461172.4933048793178132.16257002
 461215.341304883178335.29367002 460941.987104883178505.89197002
460679.7417048793178874.86057002460311.0410048793179183.65647002
 460274.997604883179507.23687002 460017.978804883180055.95667002
459571.6459048793180558.36217002 459450.507804883180840.31237002
459486.1704048793180920.25557002 459343.436962483181018.99032073

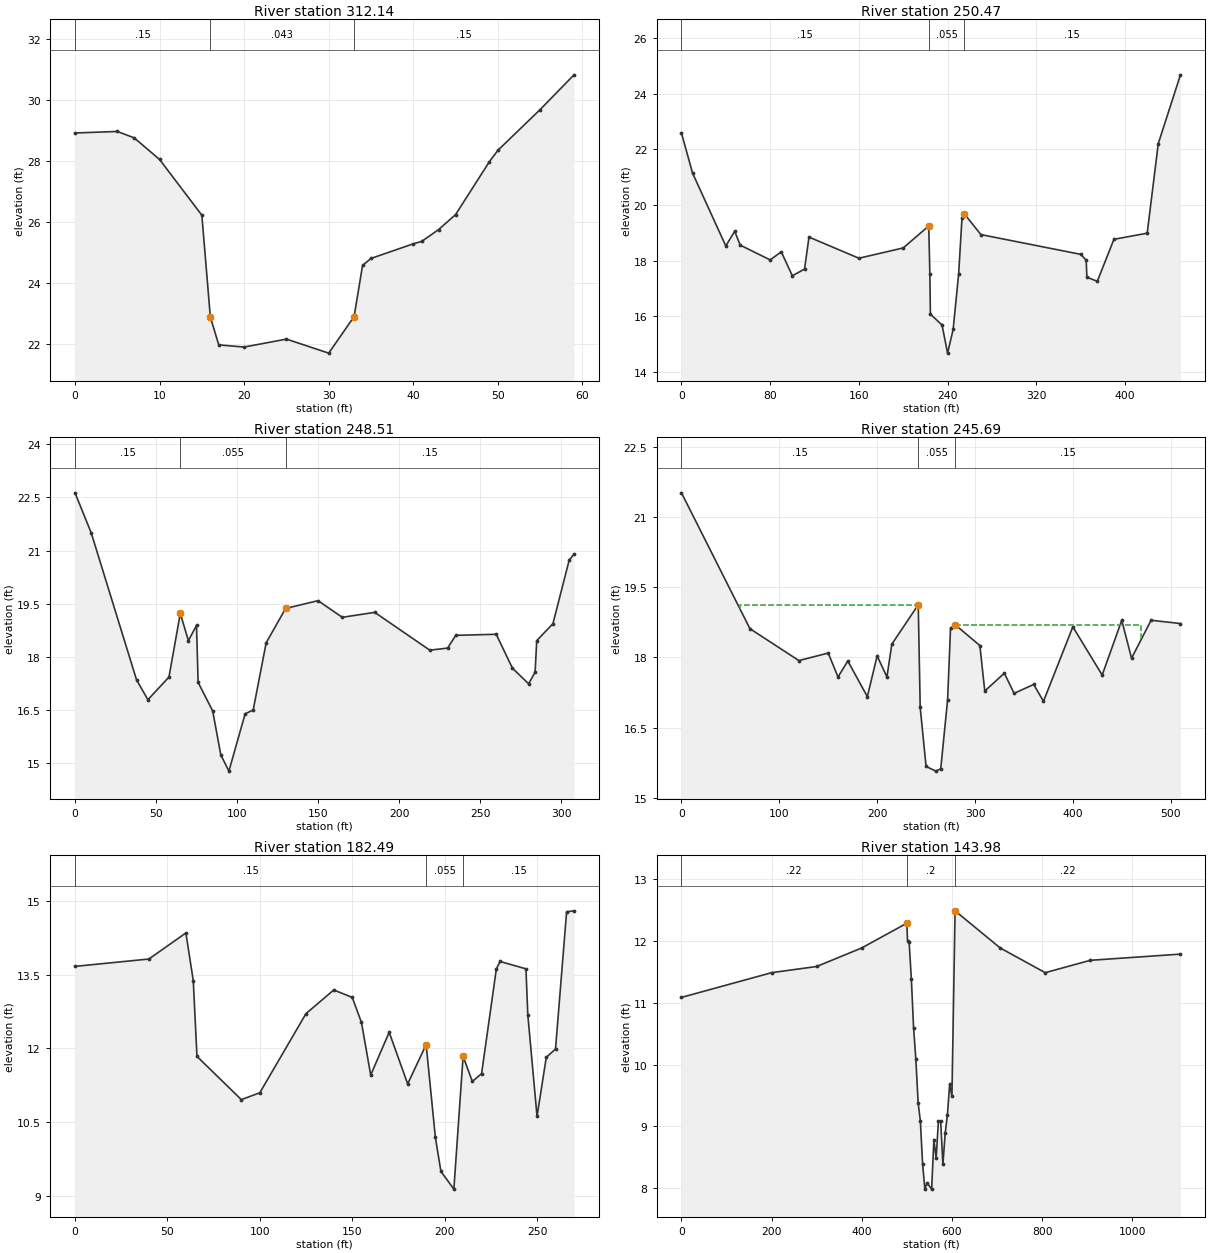
Type RM Length L Ch R = 1 ,312.14  ,6167.191,6167.191,6167.191
BEGIN DESCRIPTION:
TheSprings
END DESCRIPTION:
Node Name=TheSprings
XS GIS Cut Line= 2
461204.5570048793173492.65727002461225.0887048793173489.69387002
#Sta/Elev= 21
       0   28.92       5   28.97       7   28.76      10   28.05      15   26.22
      16   22.88      17   21.96      20   21.89      25   22.15      30   21.69
      33   22.89      34   24.57      35    24.8      40   25.28      41   25.36
      43   25.75      45   26.24      49   27.98      50   28.35      55   29.69
      59   30.83
#Mann= 3 , 0 , 0
       0     .15       0      16    .043       0      33     .15       0
Bank Sta=16,33
XS Rating Curve= 0 ,0
Exp/Cntr=0.3,0.1

Type RM Length L Ch R = 1 ,250.47  ,195.8661,195.8661,195.8661
BEGIN DESCRIPTION:
MFL_SLB_south
END DESCRIPTION:
Node Name=MFL_SLB_south
XS GIS Cut Line= 2
 461695.722804883174963.91247002461744.7818048793175039.17377002
#Sta/Elev= 30
       0  22.582      10  21.142      40  18.522      48  19.052      53  18.552
      80  18.022      90  18.312     100  17.452     111  17.692     115  18.842
     160  18.082     200  18.452     223  19.242     224  17.512   224.5  16.072
     235  15.682     240  14.672     245  15.522     250  17.532     253  19.542
     255  19.682     270  18.932     360  18.222     365  18.012   365.6  17.402
     375  17.252     390  18.762     420  18.982     430  22.202     450  24.672
#Mann= 3 , 0 , 0
       0     .15       0     223    .055       0     255     .15       0
#XS Ineff= 2 ,-1
      30     220      19     255     425    19.5
Permanent Ineff=
       F       F
Bank Sta=223,255
XS Rating Curve= 0 ,0
Exp/Cntr=0.3,0.1

Type RM Length L Ch R = 1 ,248.51  ,282.3819,282.3819,282.3819
BEGIN DESCRIPTION:
MFL_SLB_bridge
END DESCRIPTION:
Node Name=MFL_SLB_bridge
XS GIS Cut Line= 2
461657.0487048793175034.72957002461736.0472048793175081.44547002
#Sta/Elev= 30
       0  22.632      10  21.502      38  17.342      45  16.782      58  17.422
      65  19.222      70  18.452      75  18.882      76  17.272      85  16.462
      90  15.222      95  14.762     105  16.382     110  16.492     118  18.392
     130  19.362     150  19.582     165  19.112     185  19.252     219  18.182
     230  18.242     235  18.602     260  18.632     270  17.672     280  17.232
     284  17.562     285  18.452     295  18.932     305  20.722     308  20.902
#Mann= 3 , 0 , 0
       0     .15       0      65    .055       0     130     .15       0
#XS Ineff= 2 ,-1
      20      65   19.22     130     300   19.36
Permanent Ineff=
       F       F
Bank Sta=65,130
XS Rating Curve= 0 ,0
Exp/Cntr=0.3,0.1

Type RM Length L Ch R = 1 ,245.69  ,6319.948,6319.948,6319.948
BEGIN DESCRIPTION:
MFL_SLB_north
END DESCRIPTION:
Node Name=MFL_SLB_north
XS GIS Cut Line= 2
461616.7210048793175109.23877002 461714.682104883175129.98127002
#Sta/Elev= 30
       0  21.512      70  18.612     120  17.932     150  18.092     160  17.582
     170  17.922     190  17.162     200  18.032     210  17.582     215  18.282
     242  19.122     244  16.932     250  15.672     260  15.572     265  15.622
     272  17.092     275  18.622     280  18.692     305  18.252     310  17.282
     330  17.662     340  17.232     360  17.422     370  17.062     400  18.652
     430  17.622     450  18.792     460  17.982     480  18.792     510  18.722
#Mann= 3 , 0 , 0
       0     .15       0     242    .055       0     280     .15       0
#XS Ineff= 2 ,-1
      60     242   19.12     280     470   18.69
Permanent Ineff=
       F       F
Bank Sta=242,280
XS Rating Curve= 0 ,0
Exp/Cntr=0.3,0.1

Type RM Length L Ch R = 1 ,182.49  ,3850.361,3850.361,3850.361
BEGIN DESCRIPTION:
MFL_Sabol
MFL_Sabol
END DESCRIPTION:
Node Name=MFL_Sabol
XS GIS Cut Line= 2
 460724.291904883176565.62067002 461198.426104883176557.15397002
#Sta/Elev= 30
       0  13.668      40  13.818      60  14.348      64  13.378      66  11.838
      90  10.958     100  11.098     125  12.708     140  13.188     150  13.038
     155  12.528     160  11.458     170  12.328     180  11.278     190  12.078
     195  10.188     198   9.498     205   9.138     210  11.838     215  11.328
     220  11.488     228  13.618     230  13.768     244  13.618     245  12.688
     250  10.618     255  11.818     260  11.988     266  14.778     270  14.798
#Mann= 3 , 0 , 0
       0     .15       0     190    .055       0     210     .15       0
#XS Ineff= 1 ,-1
      64     120   12.08
Permanent Ineff=
       F
Bank Sta=190,210
XS Rating Curve= 0 ,0
Exp/Cntr=0.3,0.1

Type RM Length L Ch R = 1 ,143.98  ,4387.369,4387.369,4387.369
BEGIN DESCRIPTION:
LW2
END DESCRIPTION:
Node Name=LW2
XS GIS Cut Line= 2
 460933.299004883177665.03007002461212.6995048793177544.37987002
#Sta/Elev= 30
       0  11.086     200  11.486     300  11.586     400  11.886     500  12.286
   501.5  12.006     505  11.986     510  11.386     515  10.586     520  10.086
     525   9.386     530   9.086     535   8.386     540   7.986     545   8.086
     555   7.986     560   8.786     565   8.486     570   9.086     575   9.086
     580   8.386     585   8.886     590   9.186     595   9.686     600   9.486
     607  12.486     707  11.886     807  11.486     907  11.686    1107  11.786
#Mann= 3 , 0 , 0
       0     .22       0     500      .2       0     607     .22       0
Bank Sta=500,607
XS Rating Curve= 0 ,0
Exp/Cntr=0.3,0.1

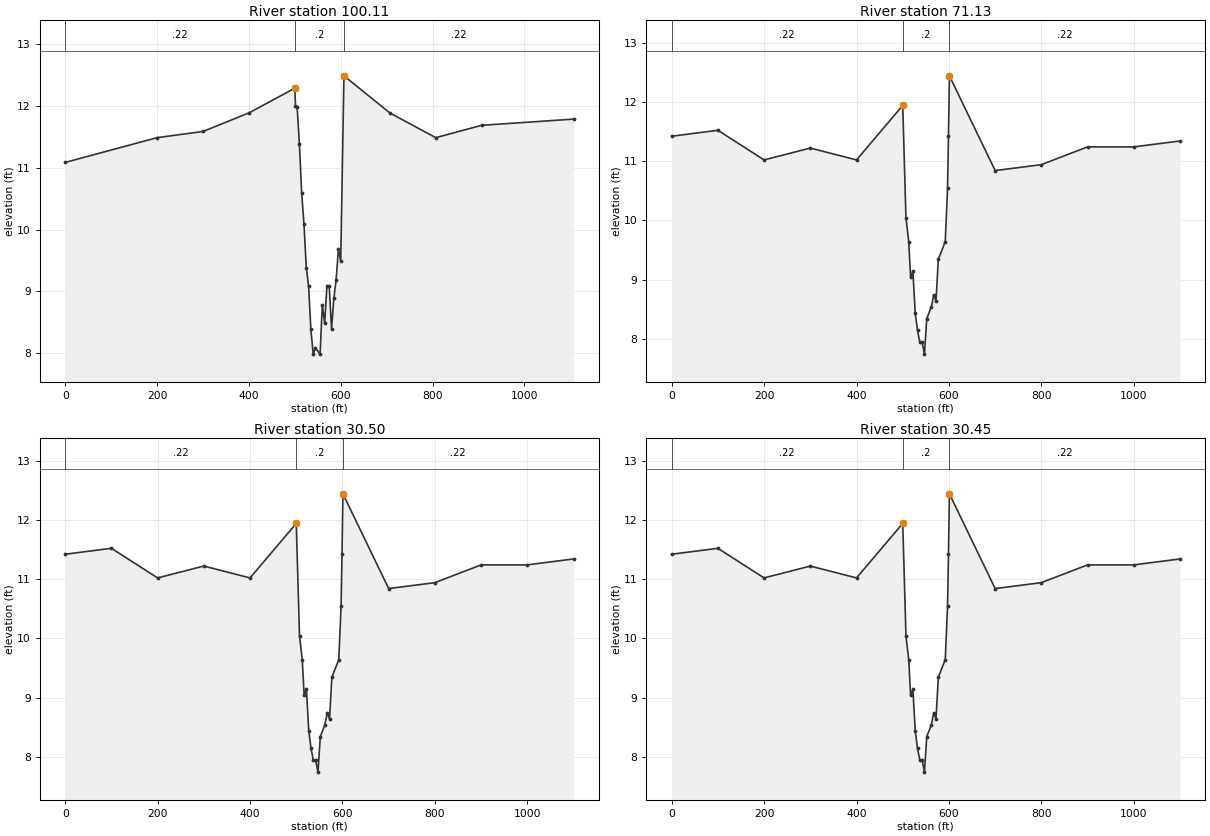
Type RM Length L Ch R = 1 ,100.11  ,2898.097,2898.097,2898.097
BEGIN DESCRIPTION:
WK19
END DESCRIPTION:
Node Name=WK19
XS GIS Cut Line= 2
 460629.076904883178693.61577002461086.2779048793178583.54887002
#Sta/Elev= 30
       0  11.086     200  11.486     300  11.586     400  11.886     500  12.286
   501.5  12.006     505  11.986     510  11.386     515  10.586     520  10.086
     525   9.386     530   9.086     535   8.386     540   7.986     545   8.086
     555   7.986     560   8.786     565   8.486     570   9.086     575   9.086
     580   8.386     585   8.886     590   9.186     595   9.686     600   9.486
     607  12.486     707  11.886     807  11.486     907  11.686    1107  11.786
#Mann= 3 , 0 , 0
       0     .22       0     500      .2       0     607     .22       0
Bank Sta=500,607
XS Rating Curve= 0 ,0
Exp/Cntr=0.3,0.1

Type RM Length L Ch R = 1 ,71.13   ,4063.156,4063.156,4063.156
BEGIN DESCRIPTION:
LW1
END DESCRIPTION:
Node Name=LW1
XS GIS Cut Line= 2
460177.6475048793179246.18327002 460425.298004883179284.28337002
#Sta/Elev= 29
       0  11.422     100  11.522     200  11.022     300  11.222     400  11.022
     500  11.942     507  10.042     513   9.642     517   9.042     522   9.142
     527   8.442     532   8.142     537   7.942     542   7.942     547   7.742
     552   8.342     562   8.542     567   8.742     572   8.642     577   9.342
     592   9.642     597  10.542     599  11.432     601  12.442     700  10.842
     800  10.942     900  11.242    1000  11.242    1100  11.342
#Mann= 3 , 0 , 0
       0     .22       0     500      .2       0     601     .22       0
Bank Sta=500,601
XS Rating Curve= 0 ,0
Exp/Cntr=0.3,0.1

Type RM Length L Ch R = 1 ,30.50   ,5,5,5
BEGIN DESCRIPTION:
WK18
END DESCRIPTION:
Node Name=WK18
XS GIS Cut Line= 2
 459515.919704883180360.70577002 459987.937304883180315.19737002
#Sta/Elev= 29
       0  11.422     100  11.522     200  11.022     300  11.222     400  11.022
     500  11.942     507  10.042     513   9.642     517   9.042     522   9.142
     527   8.442     532   8.142     537   7.942     542   7.942     547   7.742
     552   8.342     562   8.542     567   8.742     572   8.642     577   9.342
     592   9.642     597  10.542     599  11.432     601  12.442     700  10.842
     800  10.942     900  11.242    1000  11.242    1100  11.342
#Mann= 3 , 0 , 0
       0     .22       0     500      .2       0     601     .22       0
Bank Sta=500,601
XS Rating Curve= 0 ,0
Exp/Cntr=0.3,0.1

Type RM Length L Ch R = 1 ,30.45   ,3044.836,3044.836,3044.836
BEGIN DESCRIPTION:
WK18-copy
END DESCRIPTION:
XS GIS Cut Line= 2
 459515.919704883180360.70577002 459987.937304883180315.19737002
#Sta/Elev= 29
       0  11.422     100  11.522     200  11.022     300  11.222     400  11.022
     500  11.942     507  10.042     513   9.642     517   9.042     522   9.142
     527   8.442     532   8.142     537   7.942     542   7.942     547   7.742
     552   8.342     562   8.542     567   8.742     572   8.642     577   9.342
     592   9.642     597  10.542     599  11.432     601  12.442     700  10.842
     800  10.942     900  11.242    1000  11.242    1100  11.342
#Mann= 3 , 0 , 0
       0     .22       0     500      .2       0     601     .22       0
Bank Sta=500,601
XS Rating Curve= 0 ,0
Exp/Cntr=0.3,0.1

River Reach=ROK             ,ROK
Reach XY= 30
 451023.213404883181083.14707002 451213.005804883180978.54017002
451667.4719048793181512.95497002451616.6891048793181661.33587002
 451386.579704883181653.40107002 451004.122004883182350.07717002
450881.9259048793182761.10017002451048.6541048793183170.39177002
 451654.178504883183501.00377002451927.1358048793183425.22637002
452639.4171048793183613.01687002 452821.763304883183541.14077002
453009.2232048793183092.49347002453042.9461048793182603.84157002
 453025.092804883182498.70537002452899.4583048793182478.53767002
 452874.331504883182160.48417002453321.9868048793181694.31427002
453306.1172048793181509.16877002 453613.921704883181161.35967002
 453701.204604883180798.34217002453417.2045048793180367.87887002
453414.5596048793179912.94997002 453624.832004883179664.78887002
 454294.638804883179419.86777002 454666.170704883179090.68087002
455655.0262048793178870.54787002 455554.633404883178225.81147002
 456011.347704883176686.76737002456138.8371248563176526.33636962

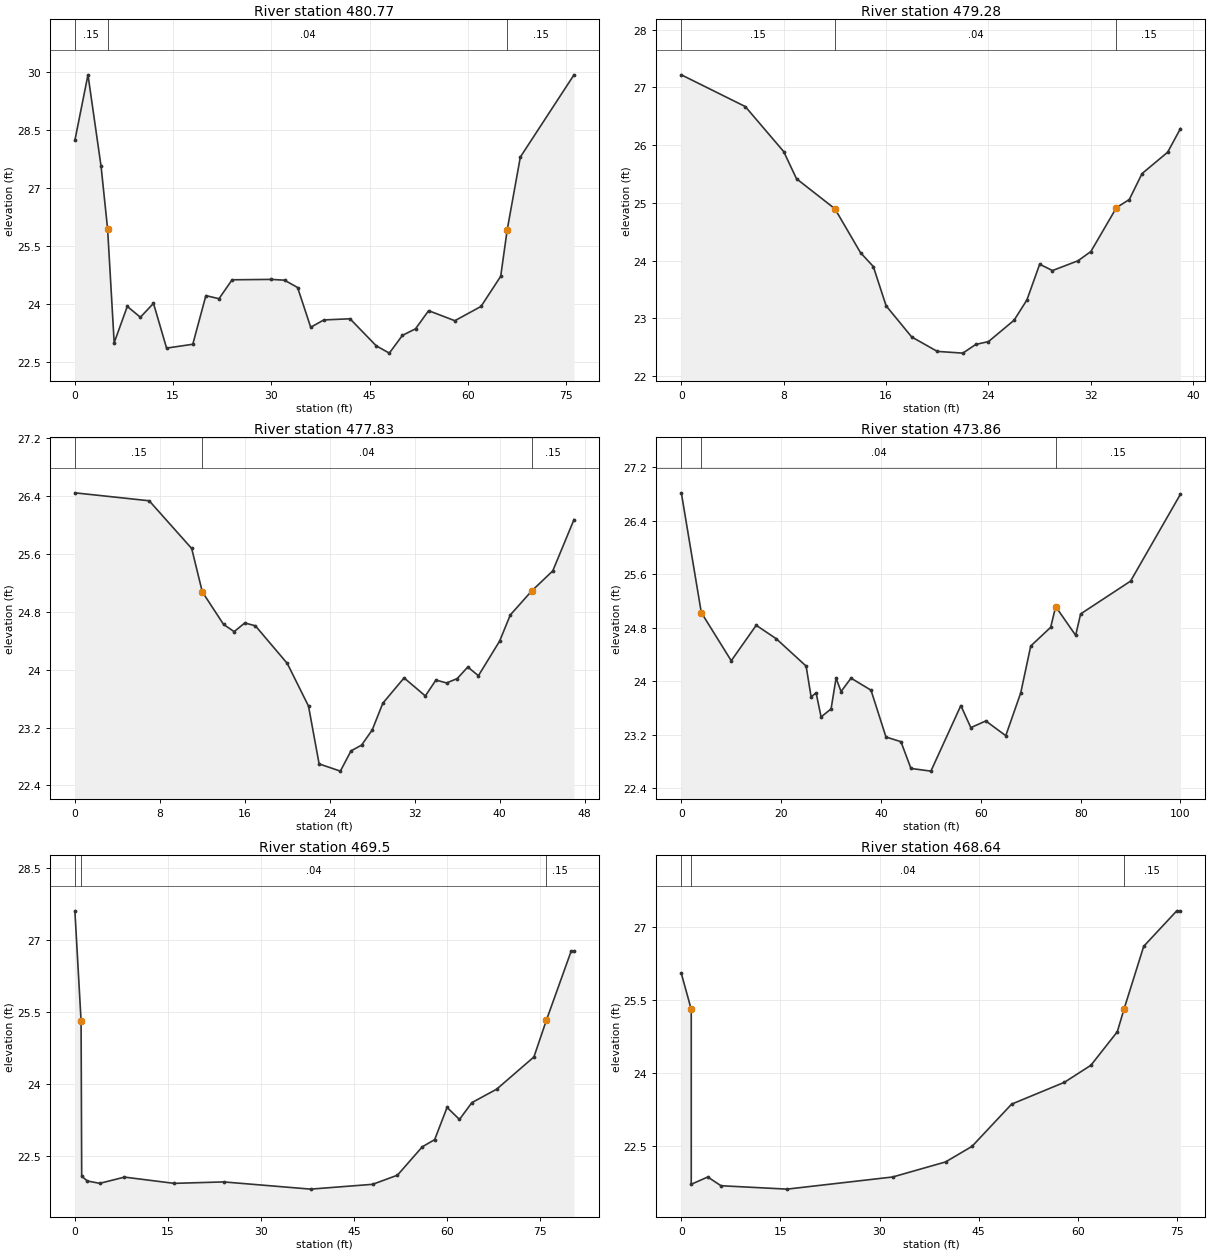
Type RM Length L Ch R = 1 ,480.77  ,149.0814,149.0814,149.0814
BEGIN DESCRIPTION:
RokSpr02
END DESCRIPTION:
Node Name=RokSpr02
XS GIS Cut Line= 2
451026.6781048793181095.07657002451022.5373048793181071.37427002
#Sta/Elev= 30
       0  28.228       2  29.928       4  27.558       5  25.928       6  22.988
       8  23.928      10  23.648      12  24.008      14  22.848      18  22.948
      20  24.208      22  24.128      24  24.618      30  24.628      32  24.608
      34  24.418      36  23.388      38  23.578      42  23.608      46  22.908
      48  22.718      50  23.178      52  23.348      54  23.818      58  23.558
      62  23.928      65  24.708      66  25.918      68  27.798   76.19  29.928
#Mann= 3 , 0 , 0
       0     .15       0       5     .04       0      66     .15       0
Bank Sta=5,66
XS Rating Curve= 0 ,0
Exp/Cntr=0.3,0.1

Type RM Length L Ch R = 1 ,479.28  ,145.1115,145.1115,145.1115
BEGIN DESCRIPTION:
RokSpr03
END DESCRIPTION:
Node Name=RokSpr03
XS GIS Cut Line= 2
451082.3677048793181066.28987002451051.4643048793181054.43647002
#Sta/Elev= 24
       0  27.218       5  26.668       8  25.888       9  25.418      12  24.898
      14  24.138      15  23.898      16  23.218      18  22.678      20  22.428
      22  22.398      23  22.548      24  22.598      26  22.968      27  23.318
      28  23.938      29  23.828      31  23.998      32  24.158      34  24.918
      35  25.058      36  25.508      38  25.878      39  26.288
#Mann= 3 , 0 , 0
       0     .15       0      12     .04       0      34     .15       0
Bank Sta=12,34
XS Rating Curve= 0 ,0
Exp/Cntr=0.3,0.1

Type RM Length L Ch R = 1 ,477.83  ,396.8176,396.8176,396.8176
BEGIN DESCRIPTION:
RokSpr04
END DESCRIPTION:
Node Name=RokSpr04
XS GIS Cut Line= 2
 451097.184404883181024.59137002 451068.609404883181013.79637002
#Sta/Elev= 28
       0  26.448       7  26.338      11  25.678      12  25.078      14  24.628
      15  24.528      16  24.648      17  24.608      20  24.088      22  23.498
      23  22.698      25  22.598      26  22.878      27  22.958      28  23.168
      29  23.538      31  23.888      33  23.638      34  23.858      35  23.818
      36  23.878      37  24.038      38  23.918      40  24.398      41  24.758
      43  25.088      45  25.368      47  26.078
#Mann= 3 , 0 , 0
       0     .15       0      12     .04       0      43     .15       0
Bank Sta=12,43
XS Rating Curve= 0 ,0
Exp/Cntr=0.3,0.1

Type RM Length L Ch R = 1 ,473.86  ,436.3189,436.3189,436.3189
BEGIN DESCRIPTION:
RokSpr05
END DESCRIPTION:
Node Name=RokSpr05
XS GIS Cut Line= 2
451175.4950048793180987.69237002451172.3109048793180957.39027002
#Sta/Elev= 30
       0  26.818       4  25.028      10  24.308      15  24.838      19  24.638
      25  24.228      26  23.768      27  23.828      28  23.468      30  23.588
      31  24.048      32  23.848      34  24.048      38  23.868      41  23.168
      44  23.098      46  22.698      50  22.658      56  23.638      58  23.308
      61  23.408      65  23.188      68  23.828      70  24.528      74  24.808
      75  25.118      79  24.688      80  25.008      90  25.498     100  26.798
#Mann= 3 , 0 , 0
       0     .15       0       4     .04       0      75     .15       0
Bank Sta=4,75
XS Rating Curve= 0 ,0
Exp/Cntr=0.3,0.1

Type RM Length L Ch R = 1 ,469.5   ,86.1877,86.1877,86.1877
BEGIN DESCRIPTION:
RokSpr08
END DESCRIPTION:
Node Name=RokSpr08
XS GIS Cut Line= 2
 451256.572004883181058.88917002451286.3376048793181034.67977002
#Sta/Elev= 21
       0  27.608       1  25.318     1.1  22.088       2  21.988       4  21.938
       8  22.068      16  21.938      24  21.968      38  21.818      48  21.918
      52  22.108      56  22.698      58  22.848      60  23.518      62  23.268
      64  23.618      68  23.898      74  24.568      76  25.328      80  26.768
   80.46  26.768
#Mann= 3 , 0 , 0
       0     .15       0       1     .04       0      76     .15       0
Bank Sta=1,76
XS Rating Curve= 0 ,0
Exp/Cntr=0.3,0.1

Type RM Length L Ch R = 1 ,468.64  ,242.6181,242.6181,242.6181
BEGIN DESCRIPTION:
RokSpr09
END DESCRIPTION:
Node Name=RokSpr09
XS GIS Cut Line= 2
 451276.415704883181079.12987002 451298.510204883181052.33677002
#Sta/Elev= 17
       0  26.048     1.5  25.308     1.5  21.708       4  21.858       6  21.678
      16  21.608      32  21.858      40  22.168      44  22.488      50  23.358
      58  23.808      62  24.158      66  24.848      67  25.308      70  26.608
      75  27.338   75.56  27.338
#Mann= 3 , 0 , 0
       0     .15       0     1.5     .04       0      67     .15       0
Bank Sta=1.5,67
XS Rating Curve= 0 ,0
Exp/Cntr=0.3,0.1

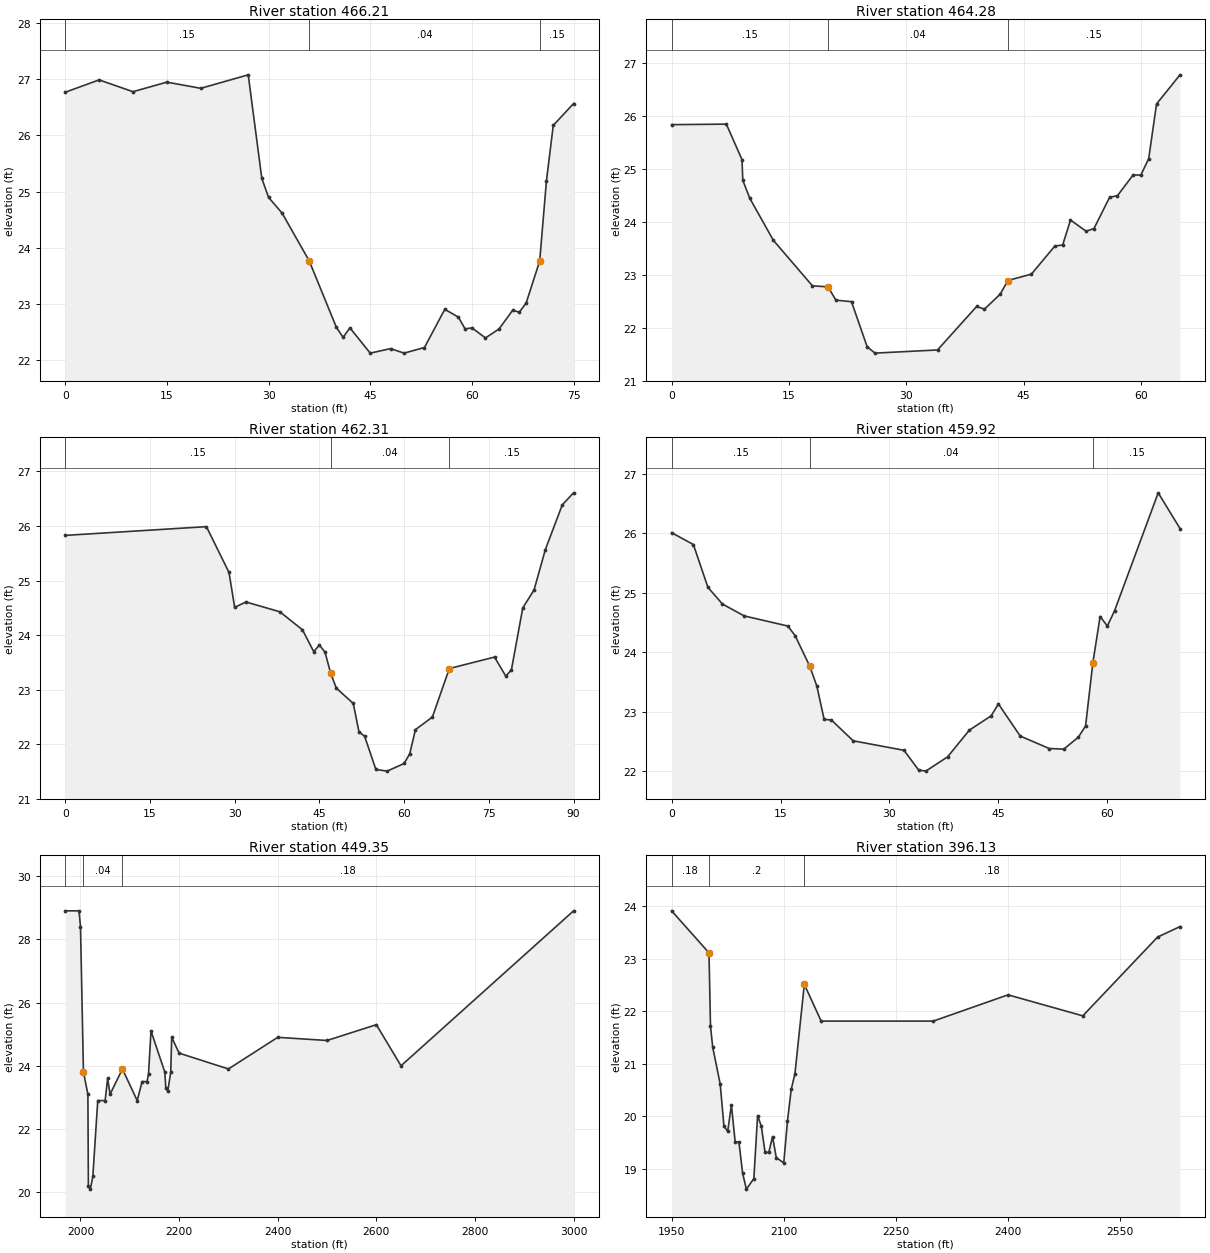
Type RM Length L Ch R = 1 ,466.21  ,193.2415,193.2415,193.2415
BEGIN DESCRIPTION:
RokSpr11
END DESCRIPTION:
Node Name=RokSpr11
XS GIS Cut Line= 2
451331.5027048793181121.98737002 451349.007504883181107.29797002
#Sta/Elev= 30
       0  26.768       5  26.988      10  26.778      15  26.948      20  26.838
      27  27.078      29  25.238      30  24.898      32  24.618      36  23.768
      40  22.588      41  22.408      42  22.578      45  22.128      48  22.208
      50  22.128      53  22.228      56  22.908      58  22.768      59  22.558
      60  22.578      62  22.398      64  22.558      66  22.888      67  22.858
      68  23.018      70  23.768      71  25.198      72  26.178      75  26.568
#Mann= 3 , 0 , 0
       0     .15       0      36     .04       0      70     .15       0
Bank Sta=36,70
XS Rating Curve= 0 ,0
Exp/Cntr=0.3,0.1

Type RM Length L Ch R = 1 ,464.28  ,196.4567,196.4567,196.4567
BEGIN DESCRIPTION:
RokSpr12
END DESCRIPTION:
Node Name=RokSpr12
XS GIS Cut Line= 2
 451376.887304883181161.36027002 451390.891104883181147.35337002
#Sta/Elev= 30
       0  25.828       7  25.838       9  25.168     9.1  24.778      10  24.438
      13  23.648      18  22.788      20  22.768      21  22.518      23  22.488
      25  21.638      26  21.518      34  21.578      39  22.398      40  22.348
      42  22.628      43  22.888      46  23.008      49  23.538      50  23.558
      51  24.028      53  23.818      54  23.868      56  24.458      57  24.488
      59  24.878      60  24.878      61  25.188      62  26.218      65  26.768
#Mann= 3 , 0 , 0
       0     .15       0      20     .04       0      43     .15       0
Bank Sta=20,43
XS Rating Curve= 0 ,0
Exp/Cntr=0.3,0.1

Type RM Length L Ch R = 1 ,462.31  ,239.5341,239.5341,239.5341
BEGIN DESCRIPTION:
RokSpr13
END DESCRIPTION:
Node Name=RokSpr13
XS GIS Cut Line= 2
451422.9117048793181205.33417002 451436.623104883181181.58607002
#Sta/Elev= 30
       0  25.828      25  25.988      29  25.148      30  24.508      32  24.608
      38  24.428      42  24.098      44  23.698      45  23.818      46  23.688
      47  23.298      48  23.028      51  22.748      52  22.228      53  22.148
      55  21.538      57  21.508      60  21.648      61  21.828      62  22.268
      65  22.498      68  23.388      76  23.598      78  23.248      79  23.368
      81  24.498      83  24.828      85  25.568      88  26.388      90  26.608
#Mann= 3 , 0 , 0
       0     .15       0      47     .04       0      68     .15       0
Bank Sta=47,68
XS Rating Curve= 0 ,0
Exp/Cntr=0.3,0.1

Type RM Length L Ch R = 1 ,459.92  ,1057.185,1057.185,1057.185
BEGIN DESCRIPTION:
RokSpr14
END DESCRIPTION:
Node Name=RokSpr14
XS GIS Cut Line= 2
451484.9297048793181229.40207002 451504.259604883181220.38617002
#Sta/Elev= 30
       0  26.008       3  25.808       5  25.088       7  24.808      10  24.608
      16  24.438      17  24.278      19  23.768      20  23.428      21  22.868
      22  22.858      25  22.508      32  22.348      34  22.018      35  21.998
      38  22.238      41  22.688      44  22.928      45  23.128      48  22.588
      52  22.378      54  22.368      56  22.568      57  22.758      58  23.818
      59  24.598      60  24.438      61  24.698      67  26.678      70  26.078
#Mann= 3 , 0 , 0
       0     .15       0      19     .04       0      58     .15       0
Bank Sta=19,58
XS Rating Curve= 0 ,0
Exp/Cntr=0.3,0.1

Type RM Length L Ch R = 1 ,449.35  ,5321.588,5321.588,5321.588
BEGIN DESCRIPTION:
ROK7
END DESCRIPTION:
Node Name=ROK7
XS GIS Cut Line= 2
 451531.470204883181508.48117002 451753.720604883181451.33097002
#Sta/Elev= 30
    1969    28.9    1997    28.9    2000    28.4    2006    23.8    2015    23.1
    2016    20.2    2020    20.1    2025    20.5    2035    22.9    2050    22.9
    2055    23.6    2060    23.1    2085    23.9    2115    22.9    2125    23.5
    2135    23.5    2138   23.75    2143    25.1    2171    23.8    2173    23.3
    2177    23.2    2183    23.8    2185    24.9    2200    24.4    2300    23.9
    2400    24.9    2500    24.8    2600    25.3    2650      24    3000    28.9
#Mann= 3 , 0 , 0
    1969     .18       0    2006     .04       0    2085     .18       0
Bank Sta=2006,2085
XS Rating Curve= 0 ,0
Exp/Cntr=0.3,0.1

Type RM Length L Ch R = 1 ,396.13  ,4586.122,4586.122,4586.122
BEGIN DESCRIPTION:
ROK6
END DESCRIPTION:
Node Name=ROK6
XS GIS Cut Line= 2
450737.7186048793182638.78337002451099.6693048793182740.38357002
#Sta/Elev= 30
    1950   23.91    2000   23.11    2002   21.71    2005   21.31    2015   20.61
    2020   19.81    2025   19.71    2030   20.21    2035   19.51    2040   19.51
    2045   18.91    2050   18.61    2060   18.81    2065   20.01    2070   19.81
    2075   19.31    2080   19.31    2085   19.61    2090   19.21    2100   19.11
    2105   19.91    2110   20.51    2115   20.81  2127.5   22.51    2150   21.81
    2300   21.81    2400   22.31    2500   21.91    2600   23.41    2630   23.61
#Mann= 3 , 0 , 0
    1950     .18       0    2000      .2       0  2127.5     .18       0
Bank Sta=2000,2127.5
XS Rating Curve= 0 ,0
Exp/Cntr=0.3,0.1