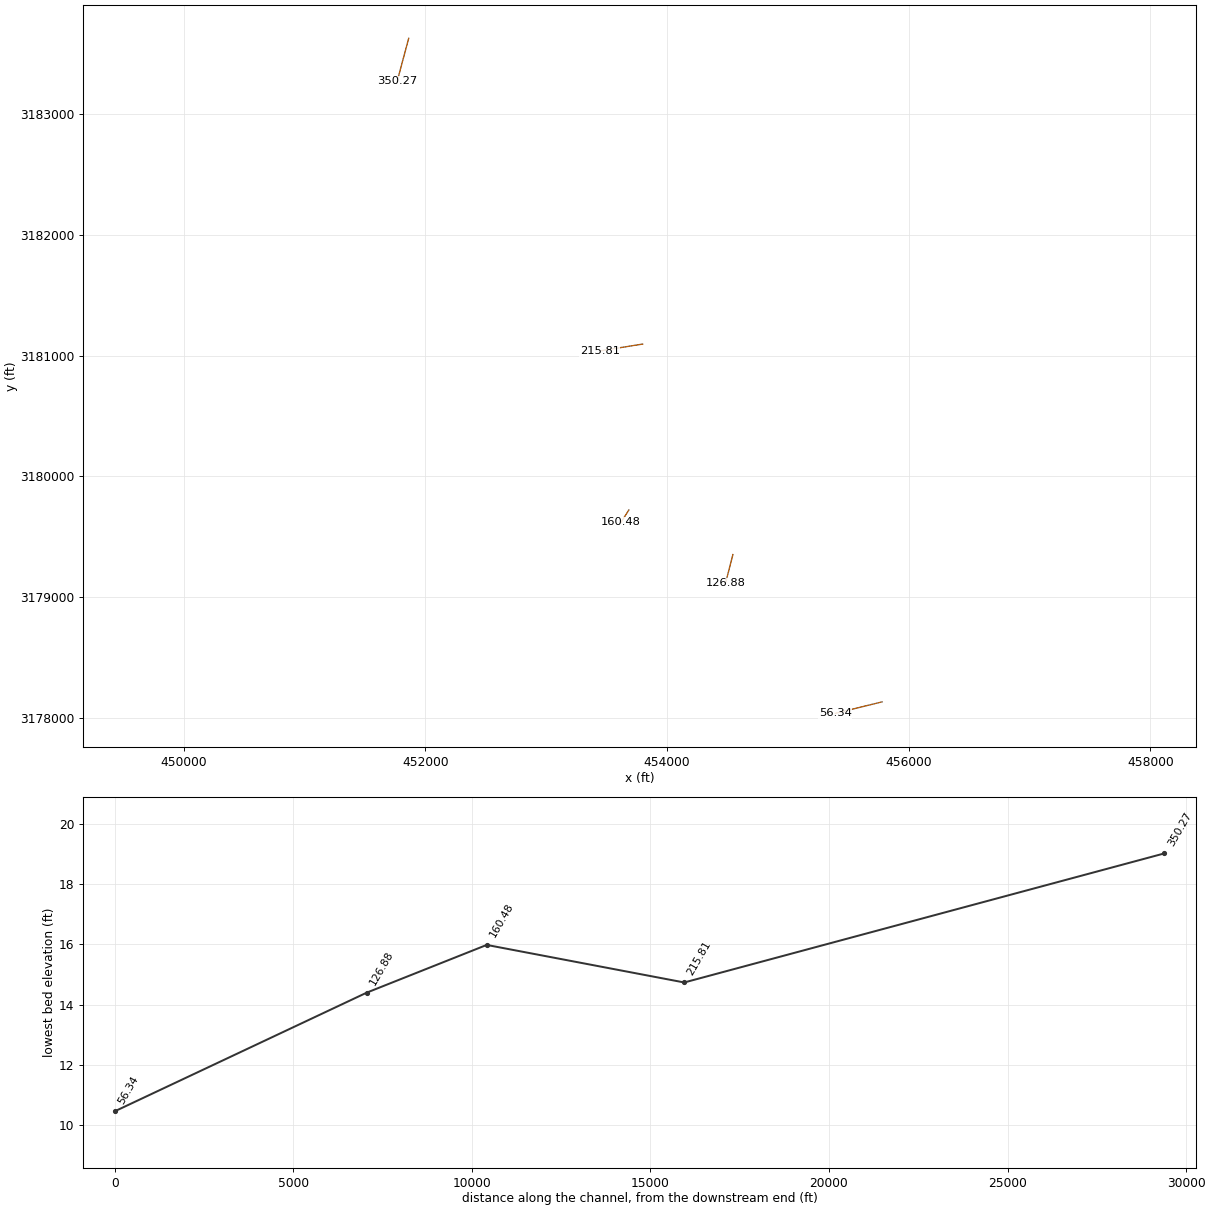
HEC-RAS study wekiva_ras.prj: wekiva_ras

--- wekiva_ras.g01 (geometry) --- (continued)

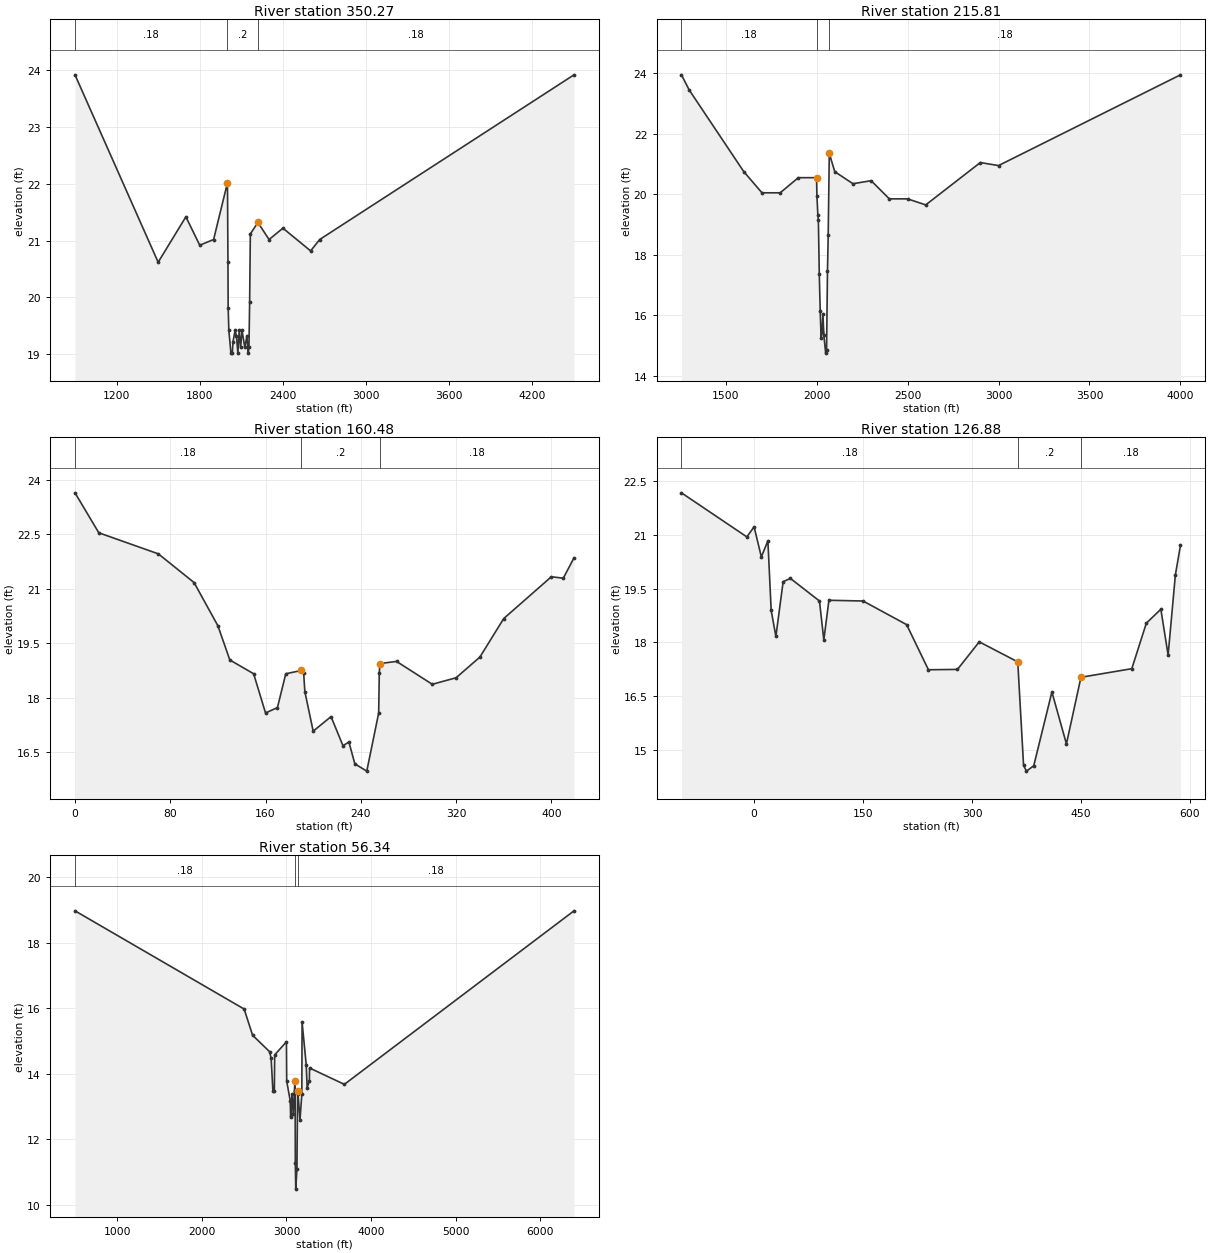
Type RM Length L Ch R = 1 ,350.27  ,13446.29,13446.29,13446.29
BEGIN DESCRIPTION:
ROK5
END DESCRIPTION:
Node Name=ROK5
XS GIS Cut Line= 2
 451861.670804883183629.38537002 451766.420704883183273.78467002
#Sta/Elev= 30
     900   23.92    1500   20.62    1700   21.42    1800   20.92    1900   21.02
    2000   22.02  2003.5   20.63    2005   19.82    2010   19.42    2025   19.02
    2035   19.02    2040   19.22    2055   19.42    2065   19.32    2075   19.02
    2085   19.42    2095   19.12    2105   19.42    2125   19.12    2140   19.32
    2150   19.02    2155   19.12    2160   19.92    2165   21.12    2220   21.32
    2300   21.02    2400   21.22    2600   20.82    2665   21.02    4500   23.92
#Mann= 3 , 0 , 0
     900     .18       0    2000      .2       0    2220     .18       0
Bank Sta=2000,2220
XS Rating Curve= 0 ,0
Exp/Cntr=0.3,0.1

Type RM Length L Ch R = 1 ,215.81  ,5532.677,5532.677,5532.677
BEGIN DESCRIPTION:
ROK4
END DESCRIPTION:
Node Name=ROK4
XS GIS Cut Line= 2
 453798.424704883181095.73027002453442.8240048793181038.58017002
#Sta/Elev= 30
  1257.5   23.94    1300   23.44    1600   20.74    1700   20.04    1800   20.04
    1900   20.54    2000   20.54    2002   19.94    2007   19.32    2010   19.14
    2015   17.34    2020   16.14    2025   15.24    2030   15.44    2035   16.04
    2040   15.34    2050   14.74    2055   14.84    2060   17.44    2064   18.64
    2070   21.34    2100   20.74    2200   20.34    2300   20.44    2400   19.84
    2500   19.84    2600   19.64    2900   21.04    3000   20.94    4000   23.94
#Mann= 3 , 0 , 0
  1257.5     .18       0    2000      .2       0    2070     .18       0
Bank Sta=2000,2070
XS Rating Curve= 0 ,0
Exp/Cntr=0.3,0.1

Type RM Length L Ch R = 1 ,160.48  ,3360.203,3360.203,3360.203
BEGIN DESCRIPTION:
ROK3
END DESCRIPTION:
Node Name=ROK3
XS GIS Cut Line= 2
 453683.837304883179720.61477002 453618.766804883179618.24147002
#Sta/Elev= 30
       0  23.645      20  22.545      70  21.965     100  21.175     120  19.985
     130  19.045     150  18.665     160  17.585     170  17.735     177  18.665
     190  18.755     192  18.685     193  18.175     200  17.085     215  17.485
     225  16.685     230  16.785     235  16.185     245  15.985     255  17.585
   255.5  18.685     256  18.945     270  19.005     300  18.375     320  18.555
     340  19.125     360  20.185     400  21.335     410  21.295     419  21.855
#Mann= 3 , 0 , 0
       0     .18       0     190      .2       0     256     .18       0
Bank Sta=190,256
XS Rating Curve= 0 ,0
Exp/Cntr=0.3,0.1

Type RM Length L Ch R = 1 ,126.88  ,7053.478,7053.478,7053.478
BEGIN DESCRIPTION:
ROK2
END DESCRIPTION:
Node Name=ROK2
XS GIS Cut Line= 2
454544.9803048793179351.14227002 454484.226104883179114.52637002
#Sta/Elev= 30
    -100  22.173     -10  20.943       0  21.223      10  20.383      19  20.833
    23.5  18.893      30  18.163      40  19.693      50  19.783      90  19.153
      96  18.063     103  19.173     150  19.153     210  18.493     240  17.233
     280  17.243     310  18.013     363  17.453     371  14.563     375  14.403
     385  14.553     410  16.613     430  15.163     450  17.023     520  17.263
     540  18.533     560  18.923     570  17.643     580  19.883     587  20.703
#Mann= 3 , 0 , 0
    -100     .18       0     363      .2       0     450     .18       0
Bank Sta=363,450
XS Rating Curve= 0 ,0
Exp/Cntr=0.3,0.1

Type RM Length L Ch R = 1 ,56.34   ,3817.881,3817.881,3817.881
BEGIN DESCRIPTION:
ROK1
END DESCRIPTION:
Node Name=ROK1
XS GIS Cut Line= 2
455779.6287048793178130.27437002455392.2779048793178035.02417002
#Sta/Elev= 30
     500   18.97    2500   15.97    2600   15.17    2800   14.67    2819   14.47
    2840   13.47    2857   13.47    2861   14.57    3000   14.97    3003   13.77
    3045   13.17    3050   12.67    3065   13.37    3080   12.77    3100   13.77
    3103   13.47    3105   11.27    3110   10.47    3124   11.07    3132   13.37
    3135   13.47    3160   12.57    3182   13.37    3185   15.57    3234   14.27
    3245   13.57    3271   13.77    3273   14.17    3685   13.67    6400   18.97
#Mann= 3 , 0 , 0
     500     .18       0    3100      .2       0    3135     .18       0
Bank Sta=3100,3135
XS Rating Curve= 0 ,0
Exp/Cntr=0.3,0.1