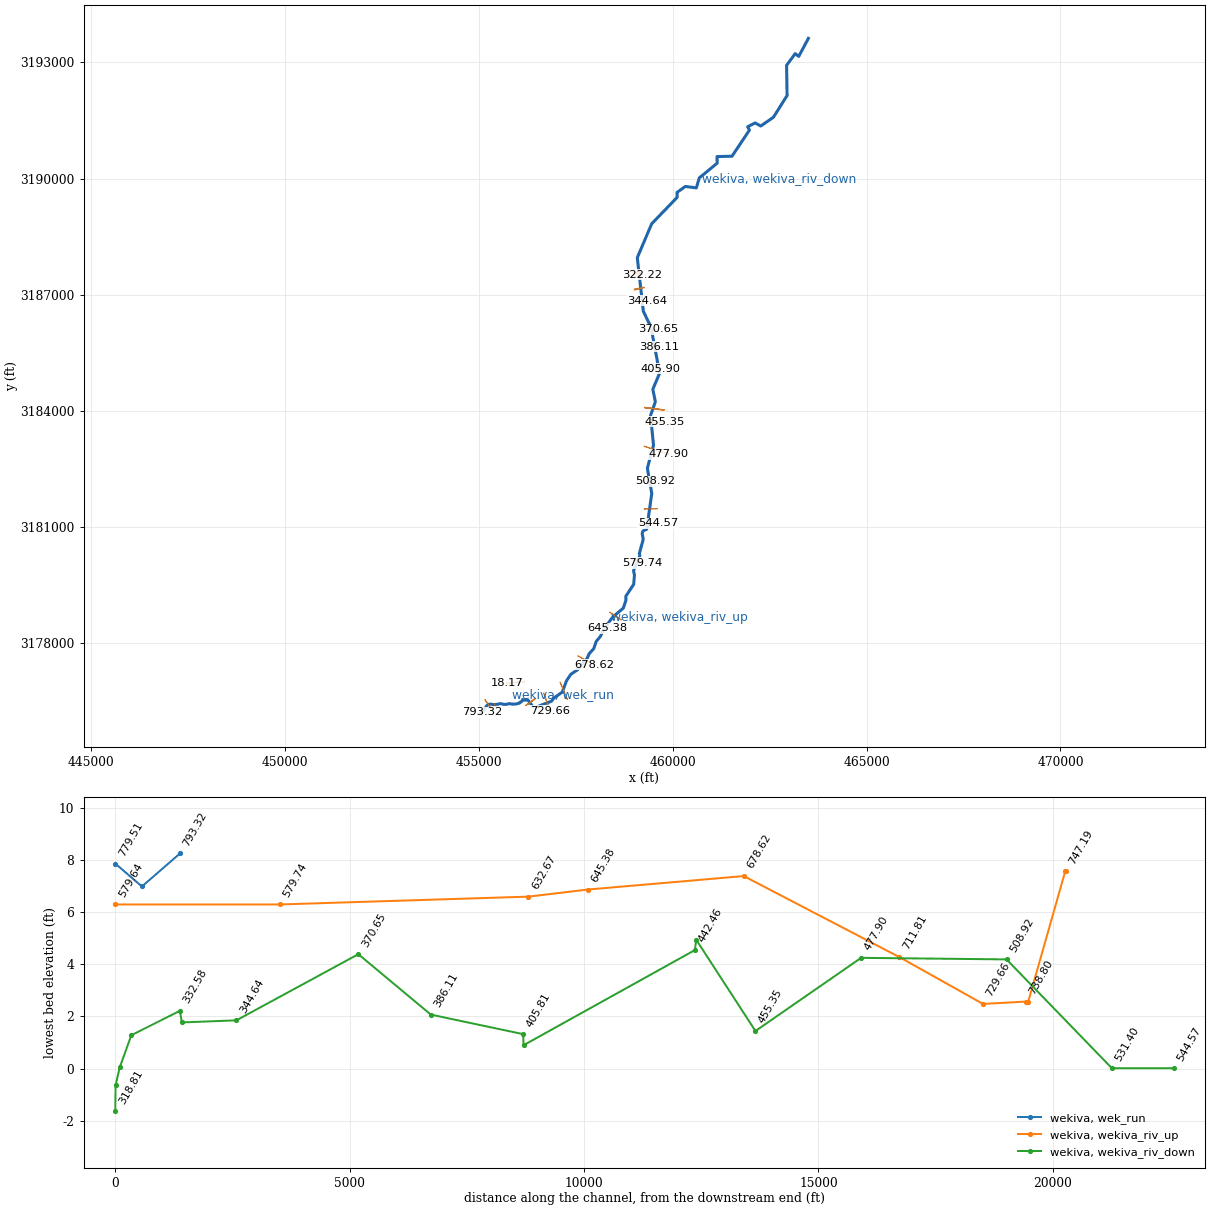
HEC-RAS study wekiva_ras.prj: wekiva_ras

--- wekiva_ras.g01 (geometry) --- (continued)

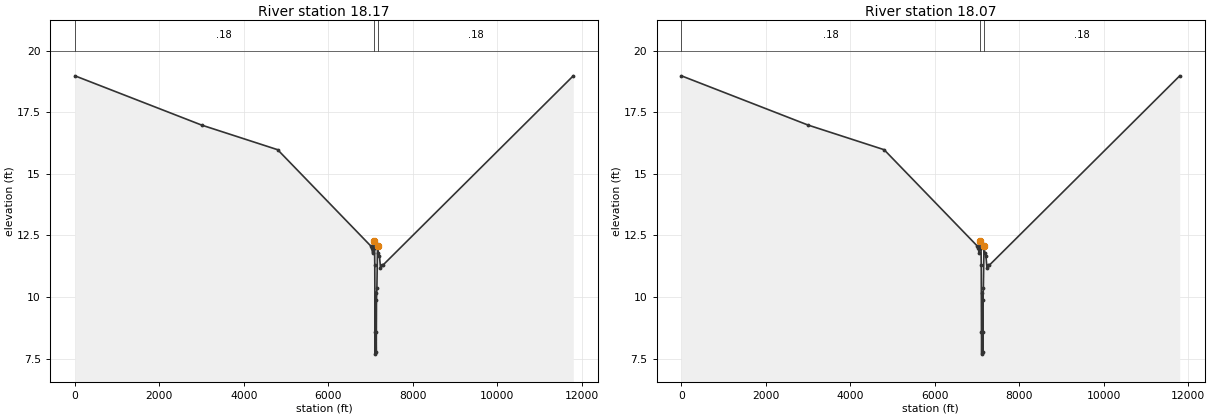
Type RM Length L Ch R = 1 ,18.17   ,10,10,10
BEGIN DESCRIPTION:
WK16
END DESCRIPTION:
Node Name=WK16
XS GIS Cut Line= 2
 456154.279404883176999.97207002455735.1786048793176961.87207002
#Sta/Elev= 23
       0   18.98    3000   16.98    4800   15.98    7000   12.08    7025   11.98
    7050   11.78    7075   12.28    7095   11.98    7100   11.28    7105    8.58
    7110    7.68    7125   10.18    7130    8.58    7135    7.78    7140    9.88
    7150   10.38    7165   12.08    7185   11.78    7210   11.68    7235   11.18
    7260   11.28    7285   11.28   11800   18.98
#Mann= 3 , 0 , 0
       0     .18       0    7075      .2       0    7165     .18       0
Bank Sta=7075,7165
XS Rating Curve= 0 ,0
Exp/Cntr=0.3,0.1

Type RM Length L Ch R = 1 ,18.07   ,1806.503,1806.503,1806.503
BEGIN DESCRIPTION:
WK16-copy
END DESCRIPTION:
XS GIS Cut Line= 2
 456154.279404883176999.97207002455735.1786048793176961.87207002
#Sta/Elev= 23
       0   18.98    3000   16.98    4800   15.98    7000   12.08    7025   11.98
    7050   11.78    7075   12.28    7095   11.98    7100   11.28    7105    8.58
    7110    7.68    7125   10.18    7130    8.58    7135    7.78    7140    9.88
    7150   10.38    7165   12.08    7185   11.78    7210   11.68    7235   11.18
    7260   11.28    7285   11.28   11800   18.98
#Mann= 3 , 0 , 0
       0     .18       0    7075      .2       0    7165     .18       0
Bank Sta=7075,7165
XS Rating Curve= 0 ,0
Exp/Cntr=0.3,0.1

River Reach=wekiva          ,wek_run
Reach XY= 30
455048.2208048793176180.16957002 455135.652104883176281.35967002
 455161.290704883176314.97967002 455186.929404883176348.59957002
 455221.114204883176393.42617002 455279.169004883176418.60717002
 455347.296904883176417.28807002 455354.239904883176411.66767002
 455361.182804883176406.04717002 455400.360904883176407.28697002
 455413.420304883176407.70017002455488.1398048793176417.28807002
455564.8629048793176432.29287002455606.0147048793176422.97217002
455647.1665048793176413.65137002 455691.231104883176411.45757002
455719.5225048793176417.37937002 455733.668104883176420.34037002
 455779.433904883176429.91987002455792.4830048793176430.21637002
 455805.532004883176430.51277002 455839.885204883176422.07207002
455912.5910048793176418.70157002455983.9726048793176426.74377002
 456062.051204883176452.13507002 456073.688804883176473.08307002
456100.9846048793176483.66277002 456127.857104883176509.68897002
 456133.653204883176518.05757002456138.8371248563176526.33636962

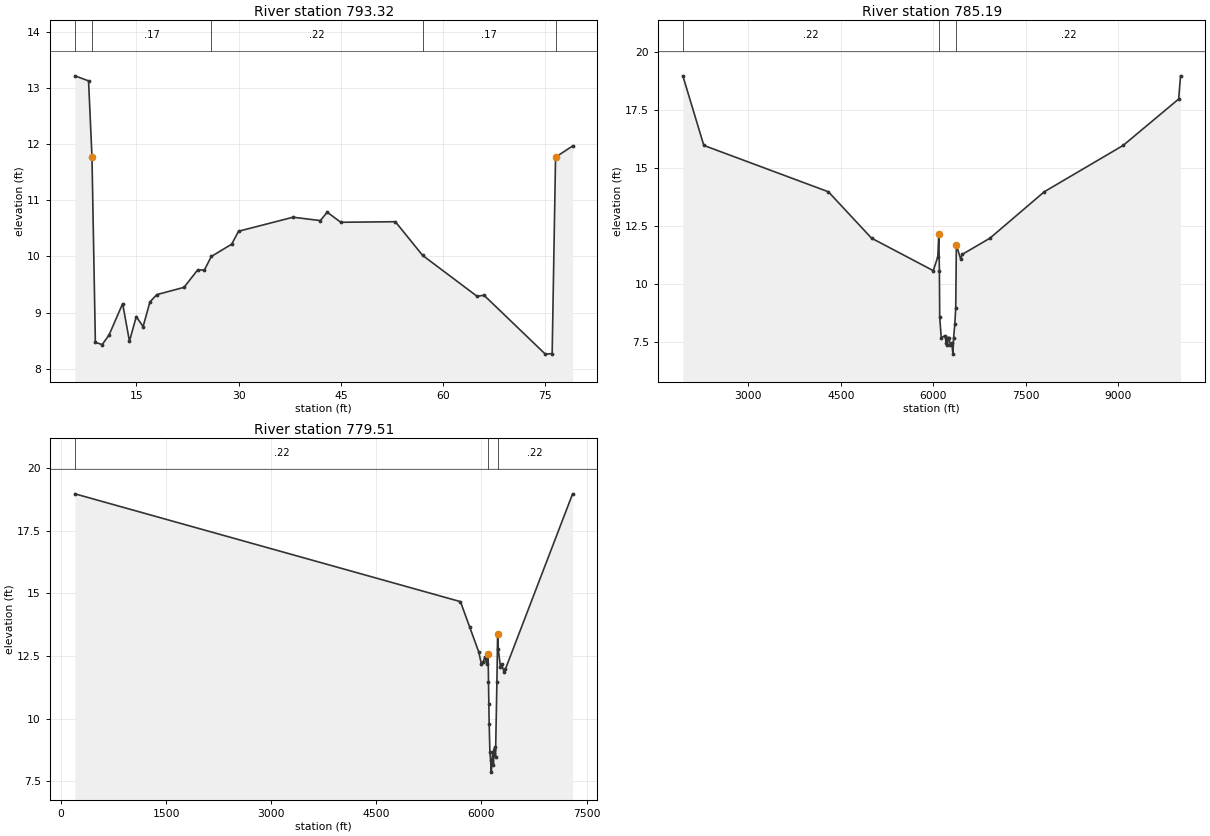
Type RM Length L Ch R = 1 ,793.32  ,813.0906,813.0906,813.0906
BEGIN DESCRIPTION:
WekSpr6
WekSpr6
END DESCRIPTION:
Node Name=WekSpr6
XS GIS Cut Line= 2
     455071.1753     3176243.645     455098.0644     3176211.408
#Sta/Elev= 30
       6   13.22       8   13.13     8.5   11.78       9    8.47      10    8.43
      11     8.6      13    9.16      14    8.49      15    8.93      16    8.75
      17    9.19      18    9.32      22    9.45      24    9.76      25    9.76
      26      10      29   10.22      30   10.45      38    10.7      42   10.64
      43   10.79      45   10.61      53   10.62      57   10.02      65    9.29
      66    9.31      75    8.26      76    8.27    76.5   11.77      79   11.97
#Mann= 5 ,-1 , 0
       6     .22       0     8.5     .17       0      26     .22       0
      57     .17       0    76.5     .22       0
Bank Sta=8.5,76.5
XS Rating Curve= 0 ,0
Exp/Cntr=0.3,0.1

Type RM Length L Ch R = 1 ,785.19  ,567.8806,567.8806,567.8806
BEGIN DESCRIPTION:
WEK13
END DESCRIPTION:
Node Name=WEK13
XS GIS Cut Line= 2
 455163.677404883176530.07117002455328.7778048793176295.12067002
#Sta/Elev= 30
    1940   18.99    2280   15.99    4300   13.99    5000   11.99    6000   10.59
    6075   11.19    6090   12.19    6100   10.59    6105    8.59    6130    7.69
    6190    7.79    6210    7.49    6220    7.69    6230    7.39    6240    7.69
    6250    7.69    6280    7.39    6300    7.49    6320    6.99    6330    7.69
    6350    8.29    6365    8.99    6375   11.69    6445   11.09    6470   11.29
    6920   11.99    7800   13.99    9080   15.99    9980   17.99   10010   18.99
#Mann= 3 , 0 , 0
    1940     .22       0    6090      .2       0    6375     .22       0
Bank Sta=6090,6375
XS Rating Curve= 0 ,0
Exp/Cntr=0.3,0.1

Type RM Length L Ch R = 1 ,779.51  ,3231.857,3231.857,3231.857
BEGIN DESCRIPTION:
WK17
END DESCRIPTION:
Node Name=WK17
XS GIS Cut Line= 2
      455414.687     3176429.959      455415.957     3176385.507
#Sta/Elev= 28
     200   18.97    5700   14.67    5830   13.67    5960   12.67    6000   12.17
    6025   12.27    6050   12.47    6075   12.17    6095   12.57    6100   11.47
    6105   10.57    6110    9.77    6120    8.67    6130    8.37    6140    7.87
    6160    8.67    6170    8.17    6180    8.77    6190    8.87    6200    8.47
    6220   11.47    6230   13.37    6240   12.77    6270   12.07    6290   12.17
    6320   11.87    6340   11.97    7300   18.97
#Mann= 3 , 0 , 0
     200     .22       0    6095      .2       0    6230     .22       0
Bank Sta=6095,6230
XS Rating Curve= 0 ,0
Exp/Cntr=0.3,0.1

River Reach=wekiva          ,wekiva_riv_up
Reach XY= 30
456138.8371248563176526.33636962 456273.222804883176523.01937002
 456397.217404883176354.37827002456471.5181048793176339.12477002
456876.9030048793176494.45407002456939.6671048793176577.53467002
 457153.375704883176727.96127002 457262.428904883177018.57457002
 457373.727804883177188.27367002457550.1979048793177310.15237002
457798.8880048793177604.91717002 457846.496804883177719.31067002
 457964.527104883177850.23497002 458031.311704883178041.66227002
 458140.415304883178173.57847002458251.4611048793178401.48007002
458459.1300048793178670.82637002 458730.236004883178901.92767002
 458795.466704883179100.95897002458794.6732048793179209.66587002
 458995.423904883179513.56897002 459016.054404883179757.96107002
458992.2500048793179866.66797002459155.8558048793180256.81797002
459141.9699048793180311.96497002 459241.551704883180675.77587002
 459214.913104883180833.89037002459235.2039048793180893.18957002
459332.6042048793180939.68187002 459343.436962483181018.99032073

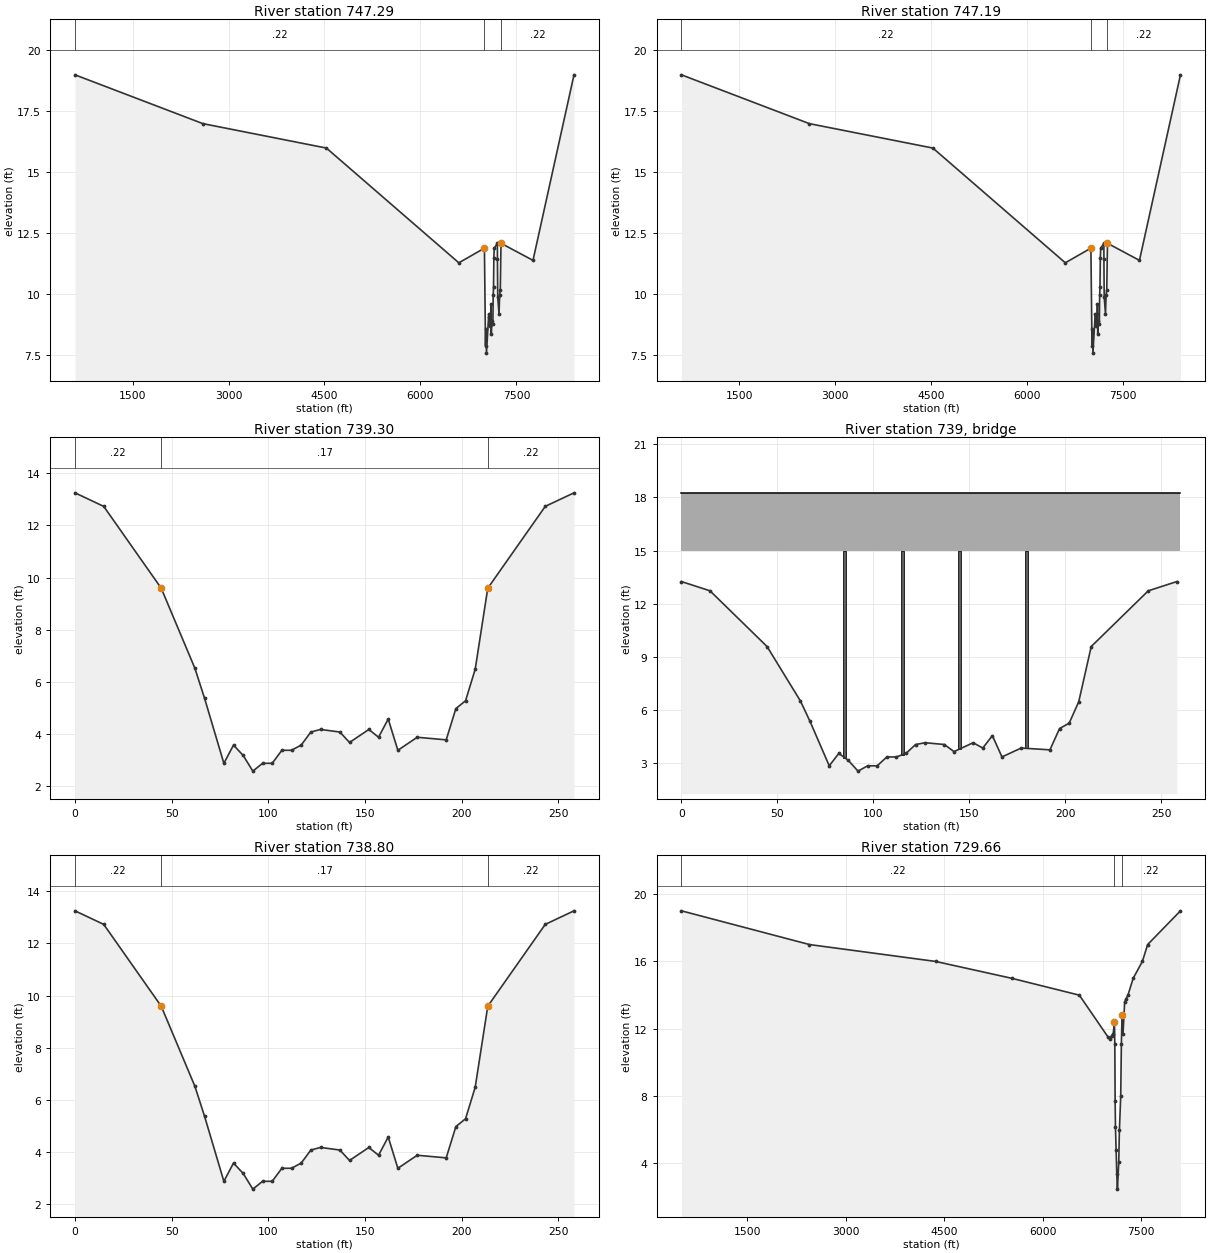
Type RM Length L Ch R = 1 ,747.29  ,10,10,10
BEGIN DESCRIPTION:
WEK12-copy
END DESCRIPTION:
XS GIS Cut Line= 2
456440.0300048793176549.12117002 456224.129604883176390.37087002
#Sta/Elev= 30
     600   18.97    2600   16.97    4530   15.97    6600   11.27    7000   11.87
    7017    7.87    7022    8.57    7032    7.57    7067    9.17    7077    9.07
    7082    8.67    7092    9.17    7097    8.87    7102    9.57    7107    8.37
    7117    8.87    7132    8.77    7137    9.97    7142   10.27    7147   11.48
  7153.5   11.87    7203   12.07  7203.5   11.41    7208    9.87    7228    9.17
    7238    9.97    7248   10.17    7259   12.07    7759   11.37    8400   18.97
#Mann= 3 , 0 , 0
     600     .22       0    7000      .2       0    7259     .22       0
Bank Sta=7000,7259
XS Rating Curve= 0 ,0
Exp/Cntr=0.3,0.1

Type RM Length L Ch R = 1 ,747.19  ,789,789,789
BEGIN DESCRIPTION:
WEK12
END DESCRIPTION:
Node Name=WEK12
XS GIS Cut Line= 2
456440.0300048793176549.12117002 456224.129604883176390.37087002
#Sta/Elev= 30
     600   18.97    2600   16.97    4530   15.97    6600   11.27    7000   11.87
    7017    7.87    7022    8.57    7032    7.57    7067    9.17    7077    9.07
    7082    8.67    7092    9.17    7097    8.87    7102    9.57    7107    8.37
    7117    8.87    7132    8.77    7137    9.97    7142   10.27    7147   11.48
  7153.5   11.87    7203   12.07  7203.5   11.41    7208    9.87    7228    9.17
    7238    9.97    7248   10.17    7259   12.07    7759   11.37    8400   18.97
#Mann= 3 , 0 , 0
     600     .22       0    7000      .2       0    7259     .22       0
Bank Sta=7000,7259
XS Rating Curve= 0 ,0
Exp/Cntr=0.3,0.1

Type RM Length L Ch R = 1 ,739.30  ,50,50,50
BEGIN DESCRIPTION:
interpolation of WEK12 amd WK15
END DESCRIPTION:
#Sta/Elev= 30
       0   13.25  14.866   12.73  44.598    9.59      62    6.52      67    5.37
      77    2.87      82    3.57      87    3.17      92    2.57      97    2.87
     102    2.87     107    3.37     112    3.37     117    3.57     122    4.07
     127    4.17     137    4.07     142    3.67     152    4.17     157    3.87
     162    4.57     167    3.37     177    3.87     192    3.77     197    4.97
     202    5.27     207    6.48   213.5    9.59 243.232   12.73 258.098   13.25
#Mann= 3 , 0 , 0
       0     .22       0  44.598     .17       0   213.5     .22       0
Bank Sta=44.598,213.5
XS Rating Curve= 0 ,0
Exp/Cntr=0.3,0.1

Type RM Length L Ch R = 3 ,739     ,,,
Bridge Culvert--1,0,-1,-1, 0
Deck Dist Width WeirC Skew NumUp NumDn MinLoCord MaxHiCord MaxSubmerge Is_Ogee
10,30,2.6,0, 2, 2, , , 0.98, 0, 0,0,,
       0     260
   18.25   18.25
      15      15
       0     260
   18.25   18.25
      15      15
Pier Skew, UpSta & Num, DnSta & Num=  ,85, 2 ,85, 2 , 0 , 0 , 0 ,,
     1.5     1.5
       0      20
     1.5     1.5
       0      20
Pier Skew, UpSta & Num, DnSta & Num=  ,115, 2 ,115, 2 , 0 , 0 , 0 ,,
     1.5     1.5
       0      20
     1.5     1.5
       0      20
Pier Skew, UpSta & Num, DnSta & Num=  ,145, 2 ,145, 2 , 0 , 0 , 0 ,,
     1.5     1.5
       0      20
     1.5     1.5
       0      20
Pier Skew, UpSta & Num, DnSta & Num=  ,180, 2 ,180, 2 , 0 , 0 , 0 ,,
     1.5     1.5
       0      20
     1.5     1.5
       0      20
BR Coef=-1 , 0 , 0 ,, 0 ,,,0.8,-1,,0,
WSPro=,,,, 1 ,,,, 0 ,,,, 0 ,,,,-1 ,-1 ,-1 , 0 , 0 , 0 , 0 , 0
BC Design=,, 0 ,, 0 ,,,,,,
BC HTab HWMax=15
BC Use User HTab Curves=0
BC User HTab FreeFlow(D)= 0

Type RM Length L Ch R = 1 ,738.80  ,914,914,914
BEGIN DESCRIPTION:
interpolation of WEK12 amd WK15
END DESCRIPTION:
#Sta/Elev= 30
       0   13.25  14.866   12.73  44.598    9.59      62    6.52      67    5.37
      77    2.87      82    3.57      87    3.17      92    2.57      97    2.87
     102    2.87     107    3.37     112    3.37     117    3.57     122    4.07
     127    4.17     137    4.07     142    3.67     152    4.17     157    3.87
     162    4.57     167    3.37     177    3.87     192    3.77     197    4.97
     202    5.27     207    6.48   213.5    9.59 243.232   12.73 258.098   13.25
#Mann= 3 , 0 , 0
       0     .22       0  44.598     .17       0   213.5     .22       0
Bank Sta=44.598,213.5
XS Rating Curve= 0 ,0
Exp/Cntr=0.3,0.1

Type RM Length L Ch R = 1 ,729.66  ,1785.368,1785.368,1785.368
BEGIN DESCRIPTION:
WK15
END DESCRIPTION:
Node Name=WK15
XS GIS Cut Line= 2
 456677.599504883176700.20887002 456838.889904883176250.62797002
#Sta/Elev= 29
     500   18.98    2450   16.98    4370   15.98    5530   14.98    6560   13.98
    7000   11.48    7025   11.38    7050   11.58    7075   11.68    7095   12.38
    7100   11.08    7105    7.68    7110    6.18    7120    4.78    7130    3.38
    7140    2.48    7160    4.08    7170    5.98    7190    7.98    7200   11.08
    7210   12.78    7225   11.68    7250   13.58    7275   13.78    7300   13.98
    7380   14.98    7520   15.98    7600   16.98    8100   18.98
#Mann= 3 , 0 , 0
     500     .22       0    7095     .17       0    7210     .22       0
Bank Sta=7095,7210
XS Rating Curve= 0 ,0
Exp/Cntr=0.3,0.1

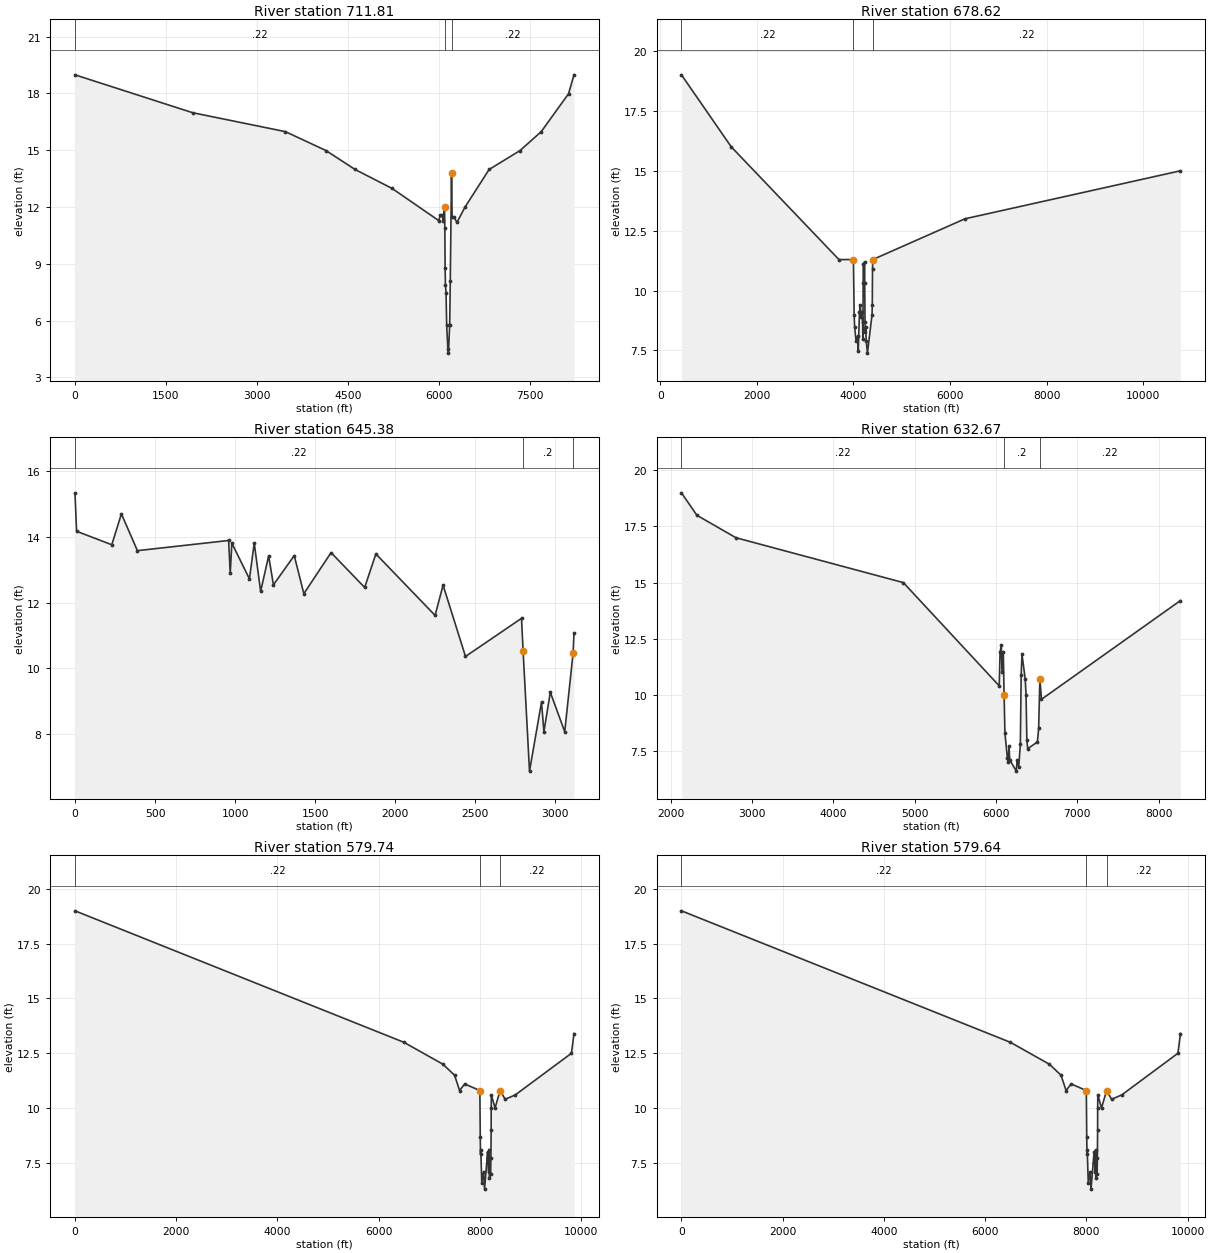
Type RM Length L Ch R = 1 ,711.81  ,3318.996,3318.996,3318.996
BEGIN DESCRIPTION:
WK14
END DESCRIPTION:
Node Name=WK14
XS GIS Cut Line= 2
457102.1360048793176981.74307002 457281.206304883176548.67217002
#Sta/Elev= 30
       1   18.98    1940   16.98    3470   15.98    4140   14.98    4620   13.98
    5230   12.98    6000   11.28    6025   11.58    6050   11.58    6075   11.28
    6095   11.98    6100   10.88    6105    8.78    6110    7.88    6120    7.48
    6130    5.78    6150    4.48    6160    4.28    6180    5.78    6190    8.08
    6210   13.78    6220   11.48    6250   11.48    6300   11.18    6430   11.98
    6830   13.98    7340   14.98    7690   15.98    8140   17.98    8230   18.98
#Mann= 3 , 0 , 0
       1     .22       0    6095     .17       0    6210     .22       0
Bank Sta=6095,6210
XS Rating Curve= 0 ,0
Exp/Cntr=0.3,0.1

Type RM Length L Ch R = 1 ,678.62  ,3324.147,3324.147,3324.147
BEGIN DESCRIPTION:
WEK11
END DESCRIPTION:
Node Name=WEK11
XS GIS Cut Line= 2
457559.9719048793177663.64977002 457967.642704883177438.85927002
#Sta/Elev= 30
     440   18.99    1470   15.99    3700   11.29    4000   11.29    4015    8.99
    4025    8.49    4055    7.89    4085    8.09    4100    7.49    4125    9.09
    4140    9.39    4165    8.89    4175    9.09    4190    8.69    4195    7.99
    4202   10.32    4203   11.09    4233   11.19  4233.5   10.32    4240    8.69
    4245    8.29    4255    8.49    4265    7.89    4290    7.39    4385    8.99
    4390    9.39    4395   10.89    4400   11.29    6310   12.99   10770   14.99
#Mann= 3 , 0 , 0
     440     .22       0    4000      .2       0    4400     .22       0
Bank Sta=4000,4400
XS Rating Curve= 0 ,0
Exp/Cntr=0.3,0.1

Type RM Length L Ch R = 1 ,645.38  ,1271.129,1271.129,1271.129
BEGIN DESCRIPTION:
MFL_Swamp
END DESCRIPTION:
Node Name=MFL_Swamp
XS GIS Cut Line= 2
 458158.511704883178457.50277002 458322.368204883178384.04377002
#Sta/Elev= 30
       0  15.343      10  14.173     230  13.763     290  14.703     390  13.583
     960  13.893     970  12.893     980  13.813    1090  12.723    1120  13.813
    1160  12.343    1210  13.423    1240  12.543    1370  13.433    1430  12.273
    1600  13.523    1810  12.463    1880  13.483    2250  11.613    2300  12.533
    2440  10.363    2790  11.523    2800  10.523    2840   6.873    2915   8.973
    2930   8.073    2970   9.273    3060   8.073  3112.5  10.473    3118  11.083
#Mann= 3 , 0 , 0
       0     .22       0    2800      .2       0  3112.5     .22       0
Bank Sta=2800,3112.5
XS Rating Curve= 0 ,0
Exp/Cntr=0.3,0.1

Type RM Length L Ch R = 1 ,632.67  ,5292.979,5292.979,5292.979
BEGIN DESCRIPTION:
WK12
END DESCRIPTION:
Node Name=WK12
XS GIS Cut Line= 2
 458386.943904883178788.98237002458672.6945048793178598.48197002
#Sta/Elev= 30
    2130      19    2320      18    2800      17    4860      15    6040    10.4
    6050    11.9    6065    12.2    6075      11    6090    11.9    6100      10
    6110     8.3    6140     7.2    6150       7    6160     7.7    6170     7.1
    6250     6.6    6260     7.1    6280     6.8    6300     7.8    6310    10.9
    6320    11.8    6360    10.7    6370      10    6380       8    6390     7.6
    6510     7.9    6525     8.5    6540    10.7    6560     9.8    8270    14.2
#Mann= 3 , 0 , 0
    2130     .22       0    6100      .2       0    6540     .22       0
Bank Sta=6100,6540
XS Rating Curve= 0 ,0
Exp/Cntr=0.3,0.1

Type RM Length L Ch R = 1 ,579.74  ,3517.093,3517.093,3517.093
BEGIN DESCRIPTION:
WEK10
END DESCRIPTION:
Node Name=WEK10
XS GIS Cut Line= 2
 458952.095004883180166.93507002 459206.095504883180065.33487002
#Sta/Elev= 30
       1      19    6500      13    7270      12    7500    11.5    7600    10.8
    7700    11.1    8000    10.8    8008     8.7    8013     7.9    8018     8.1
    8038     6.6    8073     7.1    8093     6.3    8153       8    8158     7.5
    8163     7.7    8173     7.1    8183     8.1    8188     6.8    8213       7
    8218     7.7    8223       9    8224   10.02    8227    10.6    8300      10
    8400    10.8    8500    10.4    8700    10.6    9810    12.5    9860    13.4
#Mann= 3 , 0 , 0
       1     .22       0    8000      .2       0    8400     .22       0
Bank Sta=8000,8400
XS Rating Curve= 0 ,0
Exp/Cntr=0.3,0.1

Type RM Length L Ch R = 1 ,579.64  ,3507.093,3507.093,3507.093
BEGIN DESCRIPTION:
WEK10-copy
END DESCRIPTION:
XS GIS Cut Line= 2
 458952.095004883180166.93507002 459206.095504883180065.33487002
#Sta/Elev= 30
       1      19    6500      13    7270      12    7500    11.5    7600    10.8
    7700    11.1    8000    10.8    8008     8.7    8013     7.9    8018     8.1
    8038     6.6    8073     7.1    8093     6.3    8153       8    8158     7.5
    8163     7.7    8173     7.1    8183     8.1    8188     6.8    8213       7
    8218     7.7    8223       9    8224   10.02    8227    10.6    8300      10
    8400    10.8    8500    10.4    8700    10.6    9810    12.5    9860    13.4
#Mann= 3 , 0 , 0
       1     .22       0    8000      .2       0    8400     .22       0
Bank Sta=8000,8400
XS Rating Curve= 0 ,0
Exp/Cntr=0.3,0.1

River Reach=wekiva          ,wekiva_riv_down
Reach XY= 30
 459343.436962483181018.99032073459461.8250048793181863.19517002
 459349.197004883182515.39367002 459507.275004883183107.96967002
 459431.118504883183879.39167002459555.5362048793184233.60147002
 459488.652604883184554.61977002459664.7192048793184968.68207002
459442.9677048793186158.69157002459244.9149048793186570.03217002
459089.1644048793187956.20287002459460.6590048793188831.89917002
460117.0263048793189514.91867002460112.7944048793189640.81767002
460325.9763048793189795.85487002 460611.364904883189758.82587002
460688.0680048793190017.60627002 461149.186104883190398.13777002
 461144.107804883190567.62517002 461530.691704883190577.78177002
461981.3909048793191252.35677002 461935.051704883191338.68737002
462130.1245048793191438.08417002462271.4698048793191356.83177002
 462600.447004883191585.85677002462950.8076048793192145.74307002
462938.2811048793192926.86147002 463159.926804883193226.79717002
 463251.970604883193157.49987002 463500.442604883193623.54027002

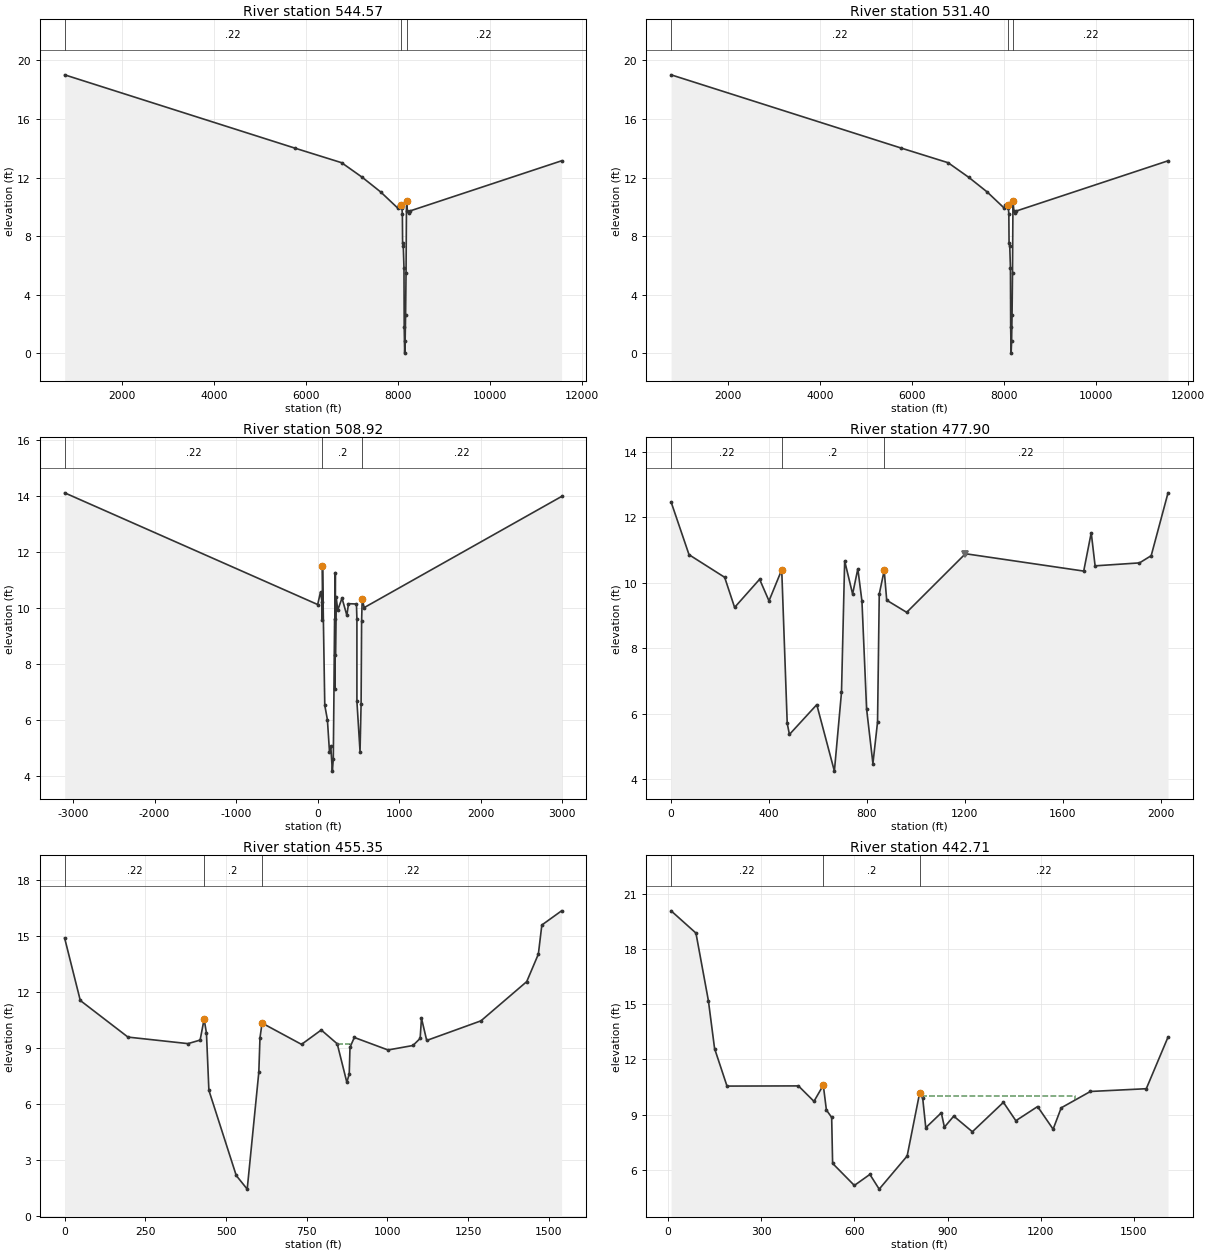
Type RM Length L Ch R = 1 ,544.57  ,1316.962,1316.962,1316.962
BEGIN DESCRIPTION:
WK11
END DESCRIPTION:
Node Name=WK11
XS GIS Cut Line= 2
 459150.085604883181066.69207002459617.8699048793181089.97547002
#Sta/Elev= 24
     760   19.01    5760   14.01    6780   13.01    7230   12.01    7630   11.01
    8000    9.91    8025   10.11    8050   10.01    8075   10.11    8090    9.91
    8100    9.51    8105    7.51    8120    7.31    8135    5.81    8140    1.81
    8150     .01    8160     .81    8170    2.61    8180    5.51    8190   10.41
    8210    9.71    8235    9.61    8260    9.71   11560   13.14
#Mann= 3 , 0 , 0
     760     .22       0    8075      .2       0    8190     .22       0
Bank Sta=8075,8190
XS Rating Curve= 0 ,0
Exp/Cntr=0.3,0.1

Type RM Length L Ch R = 1 ,531.40  ,2248.064,2248.064,2248.064
BEGIN DESCRIPTION:
WEK9-copy of WK11
END DESCRIPTION:
Node Name=WEK9-copy of WK1
XS GIS Cut Line= 2
459275.9457048793181462.33767002 459599.796304883181468.68767002
#Sta/Elev= 24
     760   19.01    5760   14.01    6780   13.01    7230   12.01    7630   11.01
    8000    9.91    8025   10.11    8050   10.01    8075   10.11    8090    9.91
    8100    9.51    8105    7.51    8120    7.31    8135    5.81    8140    1.81
    8150     .01    8160     .81    8170    2.61    8180    5.51    8190   10.41
    8210    9.71    8235    9.61    8260    9.71   11560   13.14
#Mann= 3 , 0 , 0
     760     .22       0    8075      .2       0    8190     .22       0
Bank Sta=8075,8190
XS Rating Curve= 0 ,0
Exp/Cntr=0.3,0.1

Type RM Length L Ch R = 1 ,508.92  ,3101.706,3101.706,3101.706
BEGIN DESCRIPTION:
XS20
END DESCRIPTION:
Node Name=XS20
XS GIS Cut Line= 2
 459382.978204883182113.81057002459543.4649048793182178.38367002
#Sta/Elev= 30
-3102.51   14.13       0   10.14   34.59   10.59    53.2   10.24   55.67     9.6
   58.88   11.52   86.84    6.54  119.05    6.03  144.51    4.88  160.75    5.07
  179.83    4.19  191.14    4.61  208.59    9.63  209.83    7.12  216.06   11.28
  216.99    8.35  226.31   10.41  245.77    9.94  297.99   10.37  357.95    9.75
  377.47   10.17  475.33   10.16  480.81    9.62  480.85    6.68  519.11    4.89
  532.14    6.59  538.39    9.54  545.77   10.34  569.93   10.03    2990      14
#Mann= 3 , 0 , 0
-3102.51     .22       0   58.88      .2       0  545.77     .22       0
Bank Sta=58.88,545.77
XS Rating Curve= 0 ,0
Exp/Cntr=0.3,0.1

Type RM Length L Ch R = 1 ,477.90  ,2254.396,2254.396,2254.396
BEGIN DESCRIPTION:
XS19
END DESCRIPTION:
Node Name=XS19
XS GIS Cut Line= 2
459271.5415048793183081.79267002 459890.675604883182878.71667002
#Sta/Elev= 30
       0   12.47   73.26   10.86  218.76   10.17  259.42    9.25  361.54   10.11
  399.91    9.45  451.96    10.4  474.39    5.71  483.41    5.37  595.13    6.28
  667.07    4.25  696.12    6.66  709.07   10.67  741.49    9.66   762.9   10.43
  779.69    9.44  798.65    6.15   824.5    4.48  843.38    5.75   850.4    9.66
  870.59   10.38  880.84    9.47  962.45     9.1  1202.4   10.89 1685.64   10.36
 1716.39   11.53 1732.19   10.52 1913.52   10.61 1961.33   10.83 2030.15   12.75
#Mann= 3 , 0 , 0
       0     .22       0  451.96      .2       0  870.59     .22       0
Levee=0,,,-1,1202.4,10.89,,
Bank Sta=451.96,870.59
XS Rating Curve= 0 ,0
Exp/Cntr=0.3,0.1

Type RM Length L Ch R = 1 ,455.35  ,1264.567,1264.567,1264.567
BEGIN DESCRIPTION:
XS18
END DESCRIPTION:
Node Name=XS18
XS GIS Cut Line= 2
 459315.849904883183660.11847002459780.8486048793183714.78067002
#Sta/Elev= 30
       0   14.88    48.5   11.54  196.17    9.58  382.17    9.23  419.67    9.42
  432.03   10.54  439.28     9.8  446.85    6.73  531.56    2.17  565.54    1.44
   601.5     7.7  605.09    9.54  611.58   10.33  733.81    9.19  794.93    9.96
   844.4    9.22  874.17    7.16  881.58     7.6   883.9    9.03  897.32    9.56
 1001.73    8.89 1078.97    9.13 1101.23    9.51 1105.35   10.59 1121.59     9.4
 1289.61   10.45 1431.37   12.55 1467.39   14.02 1478.21   15.58 1539.32   16.34
#Mann= 3 , 0 , 0
       0     .22       0  432.03      .2       0  611.58     .22       0
#XS Ineff= 1 ,-1
   844.4   883.9    9.22
Permanent Ineff=
       T
Bank Sta=432.03,611.58
XS Rating Curve= 0 ,0
Exp/Cntr=0.3,0.1

Type RM Length L Ch R = 1 ,442.71  ,25.1312,25.1312,25.1312
BEGIN DESCRIPTION:
MFL_RailRoad
END DESCRIPTION:
Node Name=MFL_RailRoad
XS GIS Cut Line= 3
459294.4409314813184076.20246875 459738.939404883184021.20627002
459748.8637314813184019.97836875
#Sta/Elev= 30
      10  20.083      90  18.873     130  15.203     150  12.593     190  10.553
     420  10.563     470   9.723     500  10.603     510   9.253     527    8.85
     530    6.35     600    5.15     650    5.75     680    4.95     770    6.75
     810   10.16     820    9.91     830    8.29     880     9.1     890    8.32
     920    8.92     980    8.07    1080    9.67    1120    8.67    1190    9.44
    1240    8.21    1266    9.37    1360   10.26    1540   10.41    1610   13.22
#Mann= 3 , 0 , 0
      10     .22       0     500      .2       0     810     .22       0
#XS Ineff= 1 ,-1
     820    1310      10
Permanent Ineff=
       F
Bank Sta=500,810
XS Rating Curve= 0 ,0
Exp/Cntr=0.3,0.1

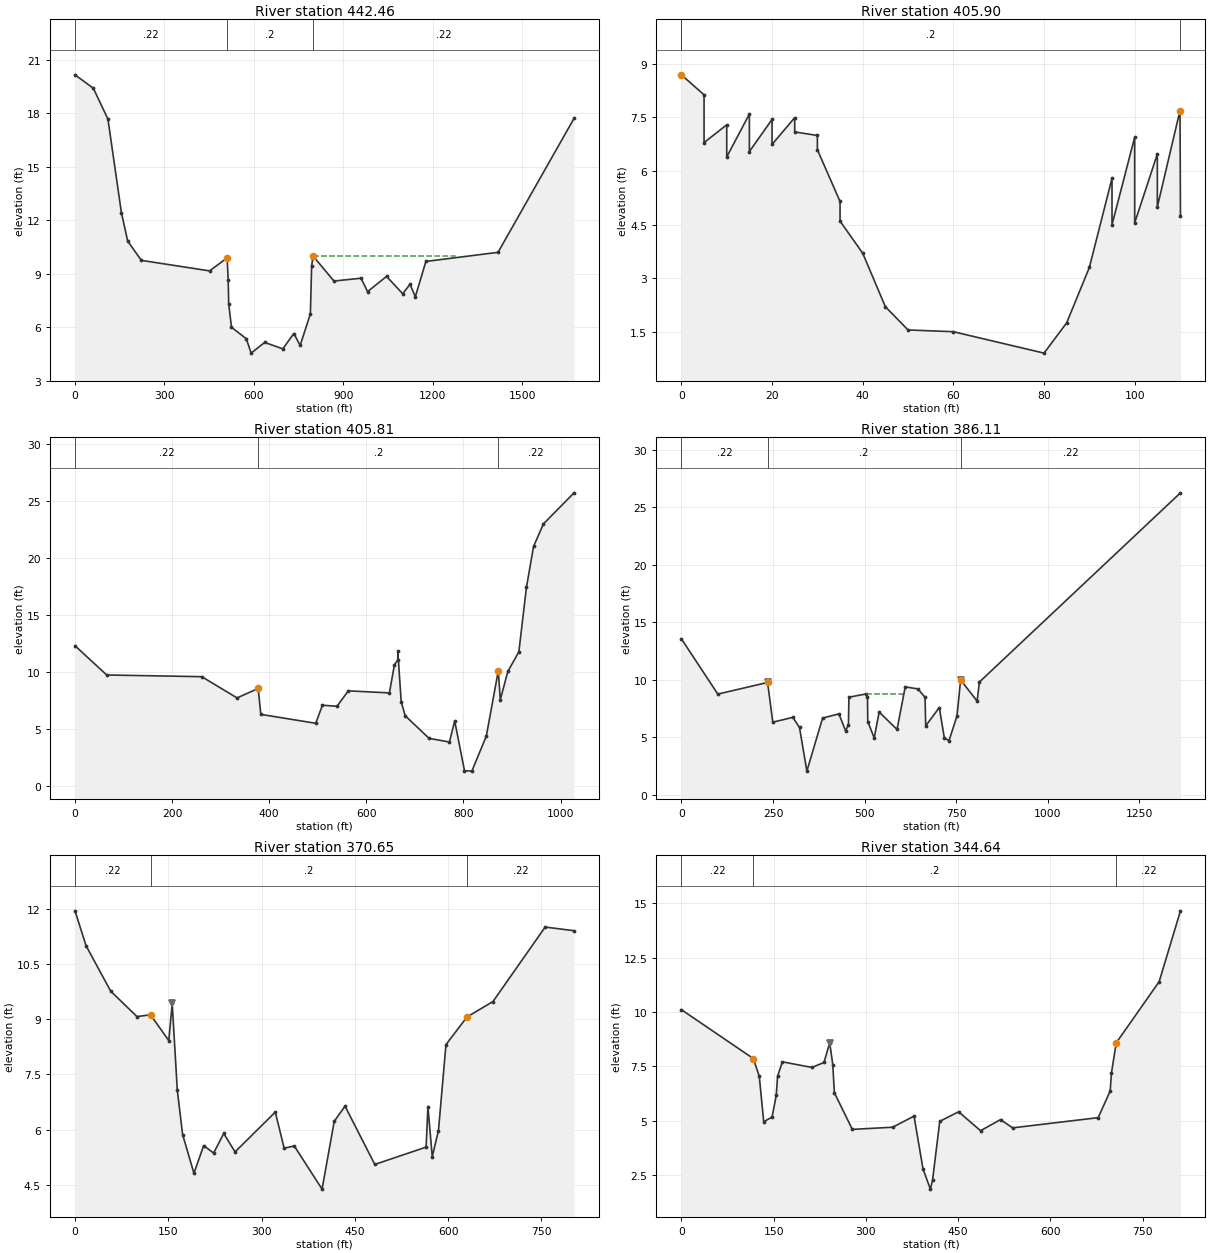
Type RM Length L Ch R = 1 ,442.46  ,3655.741,3655.741,3655.741
BEGIN DESCRIPTION:
XS17
END DESCRIPTION:
Node Name=XS17
XS GIS Cut Line= 2
 459280.081504883184086.22197002459785.7691048793184022.15867002
#Sta/Elev= 30
       0   20.15   61.42    19.4  110.54   17.67  155.69   12.43  176.82   10.83
  222.58    9.75  451.56    9.16  510.58    9.89  514.08    8.64   515.8     7.3
  525.13       6  574.67    5.36  591.09    4.55  636.43    5.15  697.31    4.79
  734.32    5.65   755.5    4.98  789.84    6.75  794.07    9.44  798.73      10
  868.83    8.59   959.7    8.75  981.77       8 1045.46    8.85 1099.65    7.88
 1124.21    8.41 1142.03    7.71 1177.45    9.69 1419.54    10.2 1674.61   17.71
#Mann= 3 , 0 , 0
       0     .22       0  510.58      .2       0  798.73     .22       0
#XS Ineff= 1 ,-1
  798.73 1274.28      10
Permanent Ineff=
       F
Bank Sta=510.58,798.73
XS Rating Curve= 0 ,0
Exp/Cntr=0.3,0.1

Type RM Length L Ch R = 1 ,405.90  ,9.2192,9.2192,9.2192
BEGIN DESCRIPTION:
MFL_RailRoadGage
END DESCRIPTION:
Node Name=MFL_RailRoadGage
XS GIS Cut Line= 2
 459603.299504883185076.81517002 459677.277104883185087.76887002
#Sta/Elev= 30
       0   8.695       5   8.135       5   6.795      10   7.295      10   6.395
      15   7.595      15   6.545      20   7.445      20   6.745      25   7.495
      25   7.095      30   6.995      30   6.595      35   5.145      35   4.595
      40   3.695      45   2.195      50   1.545      60   1.495      80    .895
      85   1.745      90   3.295      95   5.795      95   4.495     100   6.945
     100   4.545     105   6.475     105   4.995     110   7.695   110.1   4.745
#Mann= 3 , 0 , 0
       0     .22       0       0      .2       0     110     .22       0
Bank Sta=0,110
XS Rating Curve= 0 ,0
Exp/Cntr=0.3,0.1

Type RM Length L Ch R = 1 ,405.81  ,1969.554,1969.554,1969.554
BEGIN DESCRIPTION:
XS16
END DESCRIPTION:
Node Name=XS16
XS GIS Cut Line= 2
459410.1413048793185050.46617002459718.6545048793185096.86167002
#Sta/Elev= 30
       0    12.3   65.29    9.74  261.09    9.59  333.74    7.73  377.28    8.56
  382.63    6.29  495.65    5.51  509.62    7.09  539.61       7  562.74    8.35
  647.44    8.17  657.82   10.64  664.71   11.04  664.79    11.8  671.71    7.41
  679.81    6.18   729.1    4.19  771.02    3.87  781.92    5.71  802.06    1.36
  817.27    1.32  847.04    4.39  871.69   10.11  875.78    7.57   891.4   10.05
  914.04   11.77  929.68   17.42  944.36      21  964.64   22.97  1027.7   25.69
#Mann= 3 , 0 , 0
       0     .22       0  377.28      .2       0  871.69     .22       0
#XS Ineff= 1 ,-1
       0  664.79    11.8
Permanent Ineff=
       T
Bank Sta=377.28,871.69
XS Rating Curve= 0 ,0
Exp/Cntr=0.3,0.1

Type RM Length L Ch R = 1 ,386.11  ,1546.096,1546.096,1546.096
BEGIN DESCRIPTION:
XS15
END DESCRIPTION:
Node Name=XS15
XS GIS Cut Line= 2
 459399.141704883185586.81687002459651.3766048793185653.23407002
#Sta/Elev= 30
       0   13.56   99.37    8.76  235.15    9.77  249.36    6.32  304.14    6.74
  322.28    5.86  342.34    2.07  385.31    6.68  429.82    7.04     448    5.57
  455.79    6.09  457.13    8.49  504.92    8.78  507.78    8.55  508.57    6.38
  526.09    4.95  539.65     7.2  588.42    5.69  610.73    9.39  645.37    9.21
  664.84    8.48  666.61       6  703.68    7.59  717.54    4.95  730.27    4.72
  752.03    6.86  761.89    9.99  806.94    8.15  813.18    9.81 1361.78   26.24
#Mann= 3 , 0 , 0
       0     .22       0  235.15      .2       0  761.89     .22       0
Levee=-1,235.15,9.77,-1,761.89,9.99,,
#XS Ineff= 3 ,-1
  504.92  603.38    8.78  610.73  761.89    9.39  761.89  837.84    9.99
Permanent Ineff=
       F       F       F
Bank Sta=235.15,761.89
XS Rating Curve= 0 ,0
Exp/Cntr=0.3,0.1

Type RM Length L Ch R = 1 ,370.65  ,2601.247,2601.247,2601.247
BEGIN DESCRIPTION:
XS14
END DESCRIPTION:
Node Name=XS14
XS GIS Cut Line= 2
459377.3931048793186056.84457002459614.9912048793186110.32587002
#Sta/Elev= 30
       0   11.94   17.89   10.99   57.42    9.76   99.71    9.07   121.4    9.12
  150.84    8.42  156.28    9.43   164.5    7.07  173.03    5.87  191.23    4.82
  206.89    5.57  222.88    5.37  239.15     5.9  257.33     5.4  322.01    6.48
  336.28     5.5  352.58    5.56  397.24    4.39  416.81    6.23  434.15    6.64
     482    5.06  564.53    5.53  567.41    6.63   574.4    5.27  584.38    5.98
  596.42    8.31  630.25    9.06  672.03    9.48  755.96    11.5  802.37    11.4
#Mann= 3 , 0 , 0
       0     .22       0   121.4      .2       0  630.25     .22       0
Levee=-1,156.28,9.43,0,,,,
Bank Sta=121.4,630.25
XS Rating Curve= 0 ,0
Exp/Cntr=0.3,0.1

Type RM Length L Ch R = 1 ,344.64  ,1162.795,1162.795,1162.795
BEGIN DESCRIPTION:
XS13
END DESCRIPTION:
Node Name=XS13
XS GIS Cut Line= 2
 459106.813404883186782.88367002 459346.807304883186839.11017002
#Sta/Elev= 30
       0   10.11  116.97    7.86  126.63    7.05   133.9    4.95  147.48    5.17
  154.24    6.16  156.45    7.05  164.27    7.71  212.33    7.45  231.93    7.68
  241.22    8.59  246.25    7.57  248.75    6.29     278     4.6  343.64     4.7
  378.36    5.21  392.96    2.78  404.97    1.85  408.57    2.28  420.21    4.97
  450.85    5.41  486.55    4.54  519.02    5.05  538.75    4.67  677.87    5.14
  697.45    6.37  699.39    7.18  707.17    8.58  777.06    11.4   811.7   14.66
#Mann= 3 , 0 , 0
       0     .22       0  116.97      .2       0  707.17     .22       0
Levee=-1,241.22,8.59,0,,,,
Bank Sta=116.97,707.17
XS Rating Curve= 0 ,0
Exp/Cntr=0.3,0.1

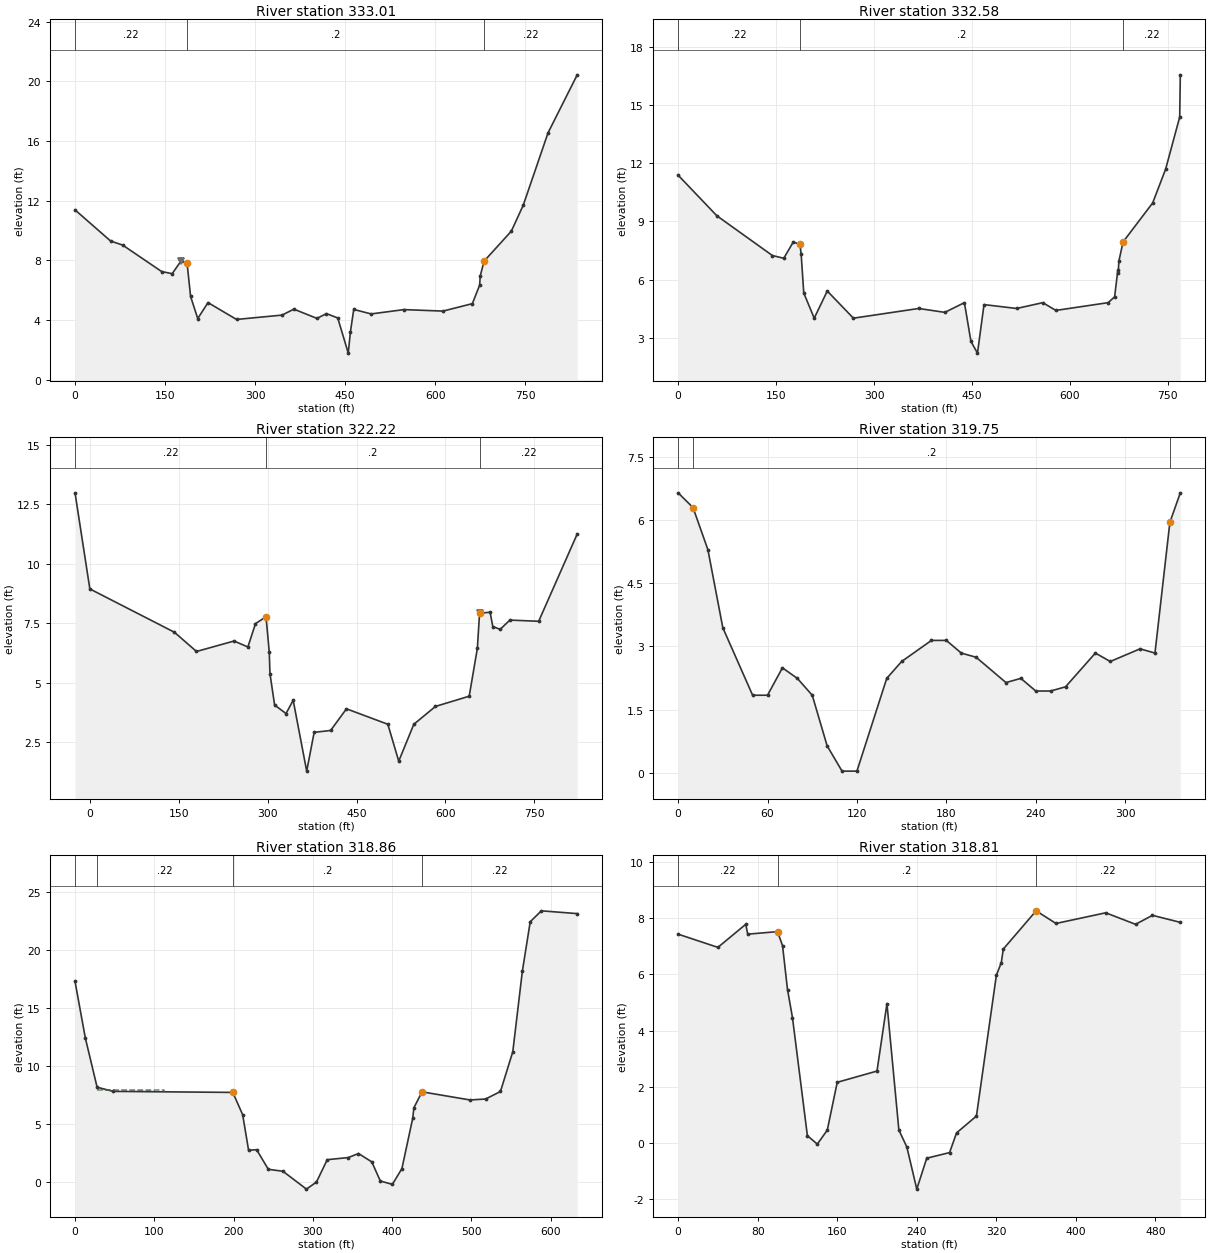
Type RM Length L Ch R = 1 ,333.01  ,43.1102,43.1102,43.1102
BEGIN DESCRIPTION:
XS12
END DESCRIPTION:
Node Name=XS12
XS GIS Cut Line= 2
 459017.819704883187123.44757002459264.5624048793187183.65137002
#Sta/Elev= 30
       0   11.38   59.29    9.29   79.28    9.02  144.39    7.24   161.8     7.1
  176.38    7.94  186.59    7.81   192.5    5.57  204.39    4.09  221.48    5.16
  268.97    4.03  344.66    4.32  364.51    4.72  402.91     4.1  418.79    4.42
  437.56    4.13  455.07    1.77  458.61    3.18   464.2     4.7  493.25     4.4
  547.84    4.69  612.88    4.59  661.78    5.09  673.87    6.33   674.9    6.95
  681.28    7.94  726.65    9.95  746.48   11.69  787.83   16.55   836.4   20.44
#Mann= 3 , 0 , 0
       0     .22       0  186.59      .2       0  681.28     .22       0
Levee=-1,176.38,7.94,0,,,,
Bank Sta=186.59,681.28
XS Rating Curve= 0 ,0
Exp/Cntr=0.3,0.1

Type RM Length L Ch R = 1 ,332.58  ,1035.531,1035.531,1035.531
BEGIN DESCRIPTION:
MFL_Flats
END DESCRIPTION:
Node Name=MFL_Flats
XS GIS Cut Line= 3
459020.8642946283187142.28128962 459030.098904883187144.19097002
459236.797342329 3187186.9353788
#Sta/Elev= 30
       0   11.38   59.29    9.29  144.39    7.24   161.8     7.1  176.38    7.94
  186.59    7.81   188.4   7.313   192.4   5.313   208.4   4.013   228.4   5.413
   268.4   4.013   368.4   4.513   408.4   4.313   438.4   4.813   448.4   2.813
   458.4   2.213   468.4   4.713   518.4   4.513   558.4   4.813   578.4   4.413
   658.4   4.813   668.4   5.113   673.4   6.513  673.87    6.33   674.9    6.95
  681.28    7.94  726.65    9.95  746.48   11.69  768.06   14.38  768.97   16.55
#Mann= 3 , 0 , 0
       0     .22       0  186.59      .2       0  681.28     .22       0
Bank Sta=186.59,681.28
XS Rating Curve= 0 ,0
Exp/Cntr=0.3,0.1

Type RM Length L Ch R = 1 ,322.22  ,247.605,247.605,247.605
BEGIN DESCRIPTION:
XS11
END DESCRIPTION:
Node Name=XS11
XS GIS Cut Line= 2
 458963.185504883187436.30517002459201.5125048793187510.18837002
#Sta/Elev= 30
     -25   12.98       0    8.94  142.61    7.12  179.95    6.31  243.27    6.75
  266.67     6.5  279.47    7.48  297.23    7.77  302.67     6.3  303.89    5.38
  311.74    4.06  331.01     3.7  343.07    4.26  365.88    1.28  378.46    2.91
  406.25    2.99  432.97     3.9  502.78    3.25  521.17     1.7  546.64    3.25
  583.13       4  640.08    4.43  653.87    6.45  657.53    7.92  675.35    7.96
  679.82    7.36  692.29    7.24  708.66    7.63  757.29    7.58   822.3   11.25
#Mann= 3 , 0 , 0
     -25     .22       0  297.23      .2       0  657.53     .22       0
Levee=0,,,-1,657.53,7.92,,
#XS Ineff= 1 ,-1
   79.45  297.23     7.7
Permanent Ineff=
       F
Bank Sta=297.23,657.53
XS Rating Curve= 0 ,0
Exp/Cntr=0.3,0.1

Type RM Length L Ch R = 1 ,319.75  ,88.8451,88.8451,88.8451
BEGIN DESCRIPTION:
MFL_SR46E
END DESCRIPTION:
Node Name=MFL_SR46E
XS GIS Cut Line= 2
459015.1934048793187548.55247002 459144.574904883187545.90667002
#Sta/Elev= 29
       0    6.64      10    6.29      20    5.29      30    3.44      50    1.84
      60    1.84      70    2.49      80    2.24      90    1.84     100     .64
     110     .04     120     .04     140    2.24     150    2.64     170    3.14
     180    3.14     190    2.84     200    2.74     220    2.14     230    2.24
     240    1.94     250    1.94     260    2.04     280    2.84     290    2.64
     310    2.94     320    2.84     330    5.94     337    6.64
#Mann= 3 , 0 , 0
       0     .22       0      10      .2       0     330     .22       0
Bank Sta=10,330
XS Rating Curve= 0 ,0
Exp/Cntr=0.3,0.1

Type RM Length L Ch R = 1 ,318.86  ,5.4462,5.4462,5.4462
BEGIN DESCRIPTION:
XS10
END DESCRIPTION:
Node Name=XS10
XS GIS Cut Line= 2
458974.1189048793187575.68317002 459166.370904883187566.64927002
#Sta/Elev= 30
       0   17.26   12.98   12.39   27.84    8.14   48.09    7.78     199    7.69
  211.42    5.77  218.91     2.7  229.06    2.75  243.78    1.06  262.24     .89
   291.9    -.65  304.49    -.04  318.13    1.89  344.52    2.07  357.51    2.42
  374.28     1.7  385.06     .05  400.25    -.24  412.27    1.12  425.87    5.45
  427.42    6.37  437.69    7.74   498.1    7.04  517.84    7.12  536.57    7.77
  552.12    11.2  564.22   18.16  574.11   22.41  588.18   23.35  633.37   23.11
#Mann= 4 , 0 , 0
       0     .22       0   27.84     .22       0     199      .2       0
  437.69     .22       0
#XS Ineff= 1 ,-1
   27.84  112.66     7.9
Permanent Ineff=
       F
Bank Sta=199,437.69
XS Rating Curve= 0 ,0
Exp/Cntr=0.5,0.3

Type RM Length L Ch R = 1 ,318.81  ,61.1549,61.1549,61.1549
BEGIN DESCRIPTION:
MFL_SR46B
END DESCRIPTION:
Node Name=MFL_SR46B
XS GIS Cut Line= 2
 458972.529304883187577.41857002459149.2051048793187568.68737002
#Sta/Elev= 30
       0    7.43      40    6.96      68    7.78      70    7.43     100    7.52
     105    7.02     110    5.46     115    4.46     130     .26     140    -.04
     150     .46     160    2.16     200    2.56     210    4.96     222     .46
     230    -.14     240   -1.64     250    -.54     273    -.34     280     .36
     300     .96     320    5.96     325    6.42     327     6.9     360    8.26
     380    7.81     430    8.19     460    7.78     477     8.1     505    7.85
#Mann= 3 , 0 , 0
       0     .22       0     100      .2       0     360     .22       0
Bank Sta=100,360
XS Rating Curve= 0 ,0
Exp/Cntr=0.5,0.3