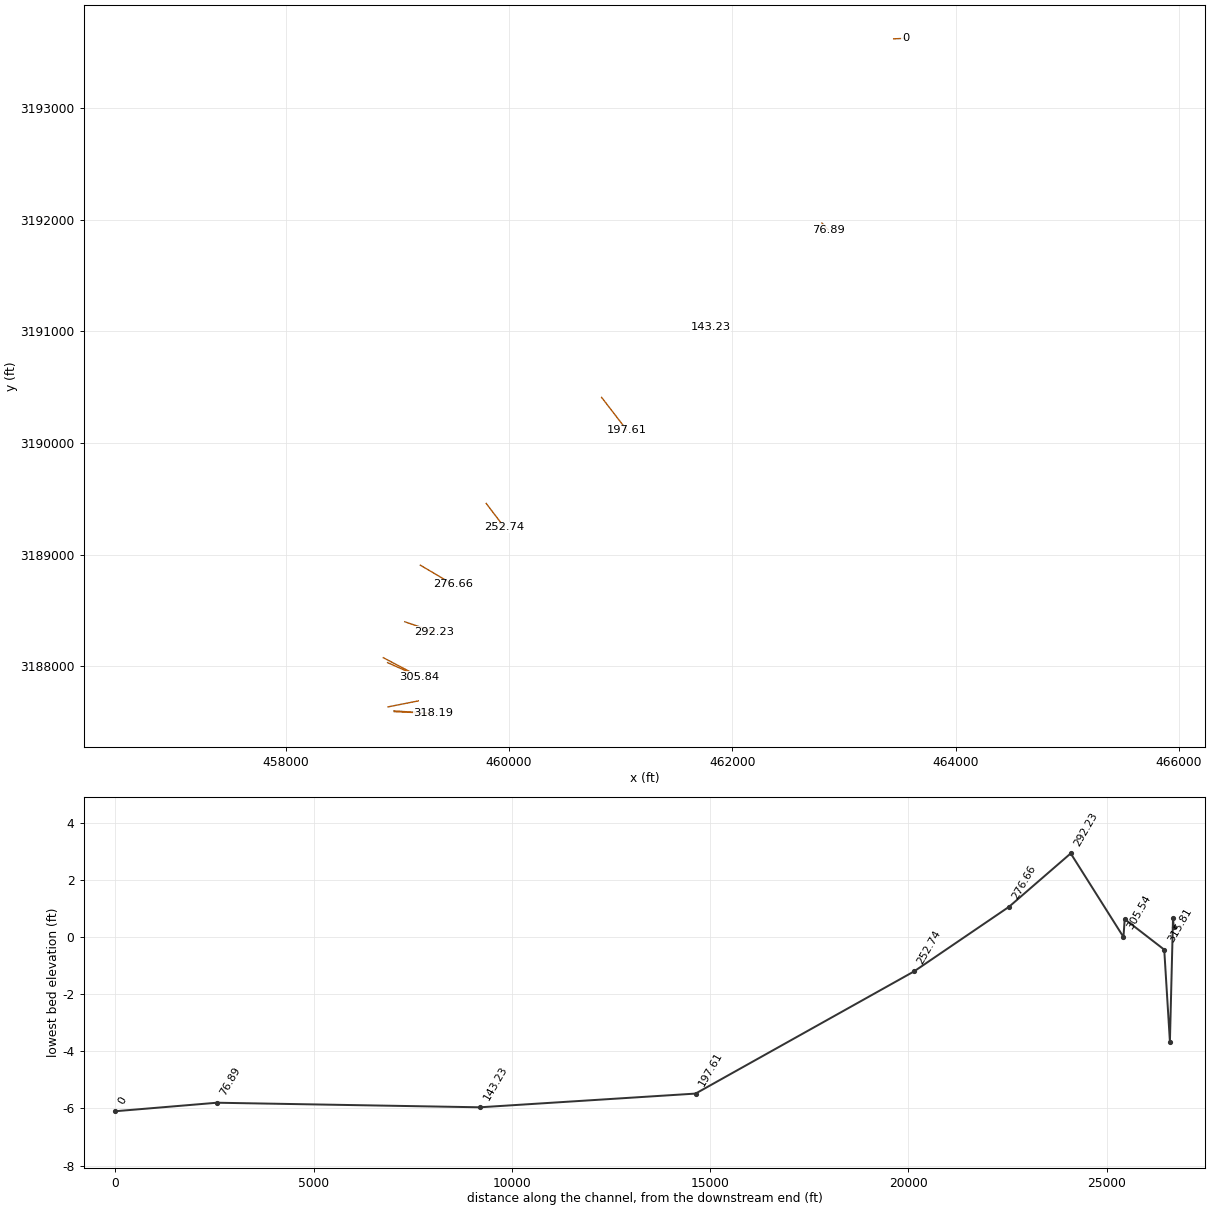
HEC-RAS study wekiva_ras.prj: wekiva_ras

--- wekiva_ras.g01 (geometry) --- (continued)

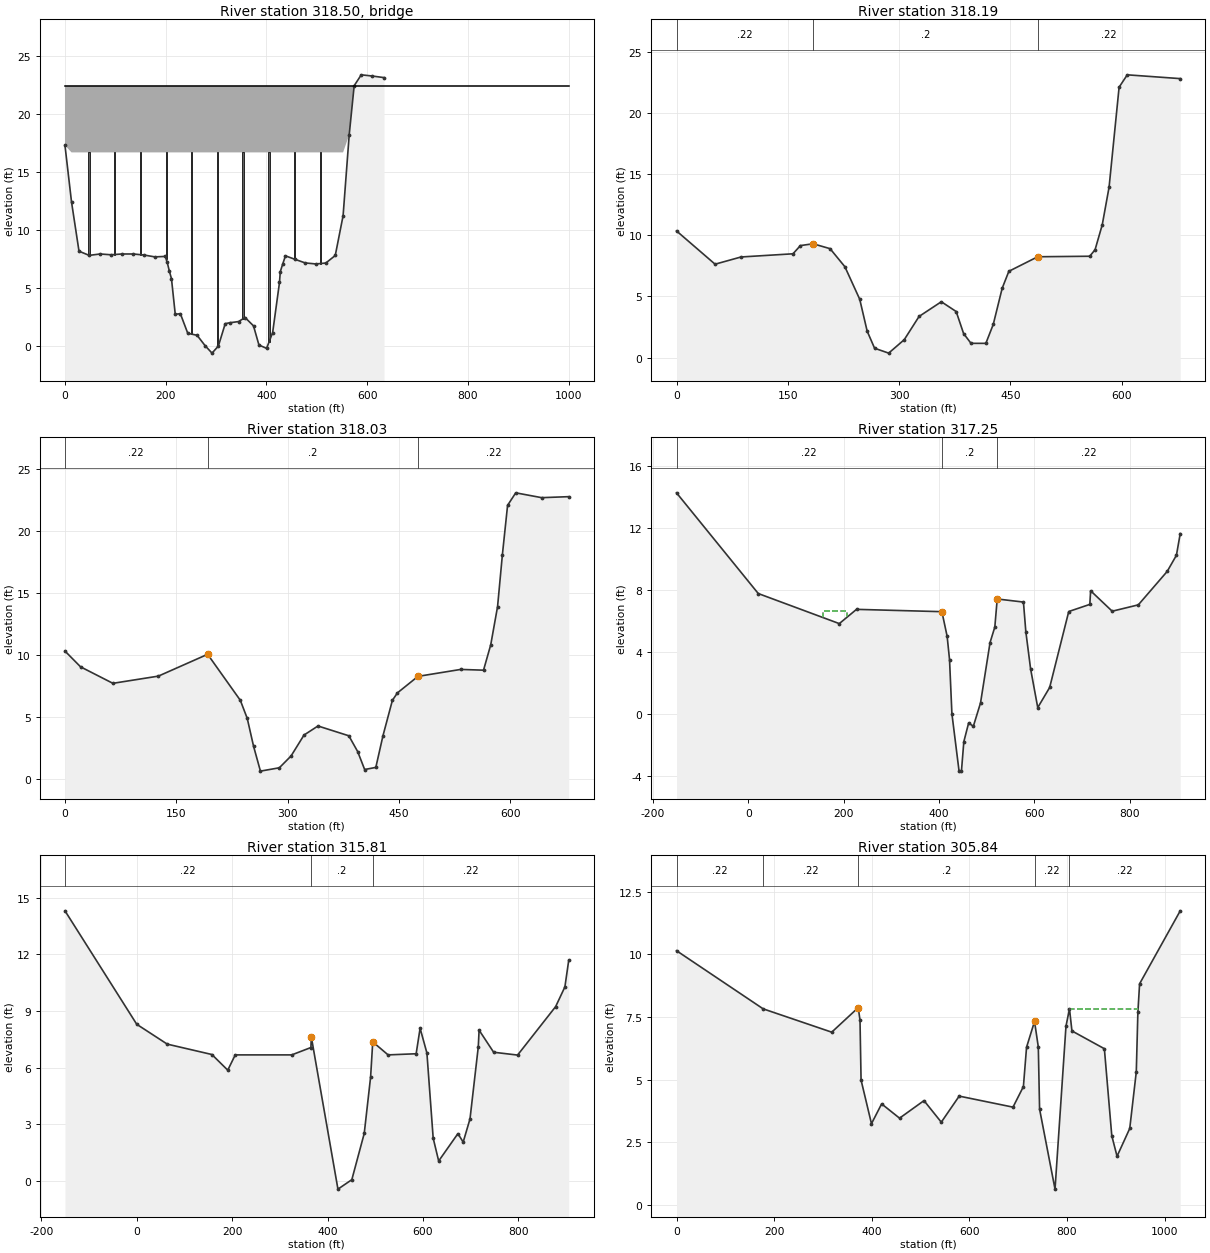
Type RM Length L Ch R = 3 ,318.50  ,,,
BEGIN DESCRIPTION:
SR46
SR46
END DESCRIPTION:
Bridge Culvert--1,0,-1,-1, 0
Deck Dist Width WeirC Skew NumUp NumDn MinLoCord MaxHiCord MaxSubmerge Is_Ogee
10,42,2.6,0, 2, 2, , , 0.98, 0, 0,0,,
       0    1000
   22.41   22.41
   16.66   16.66
       0    1000
   22.41   22.41
   16.66   16.66
Pier Skew, UpSta & Num, DnSta & Num=  ,47.6, 2 ,70.62, 2 , 0 , 0 , 0 ,,
    2.51    2.51
      -5      20
    2.51    2.51
      -5      20
Pier Skew, UpSta & Num, DnSta & Num=  ,98.58, 2 ,121.24, 2 , 0 , 0 , 0 ,,
    2.59    2.59
      -5      20
    2.59    2.59
      -5      20
Pier Skew, UpSta & Num, DnSta & Num=  ,149.66, 2 ,172.34, 2 , 0 , 0 , 0 ,,
    2.76    2.76
      -5      20
    2.76    2.76
      -5      20
Pier Skew, UpSta & Num, DnSta & Num=  ,200.99, 2 ,223.47, 2 , 0 , 0 , 0 ,,
    2.49    2.49
      -5      20
    2.49    2.49
      -5      20
Pier Skew, UpSta & Num, DnSta & Num=  ,251.54, 2 ,274.63, 2 , 0 , 0 , 0 ,,
    2.88    2.88
      -5      20
    2.88    2.88
      -5      20
Pier Skew, UpSta & Num, DnSta & Num=  ,302.68, 2 ,325.54, 2 , 0 , 0 , 0 ,,
    2.56    2.56
      -5      20
    2.56    2.56
      -5      20
Pier Skew, UpSta & Num, DnSta & Num=  ,353.48, 2 ,376.5, 2 , 0 , 0 , 0 ,,
    2.72    2.72
      -5      20
    2.72    2.72
      -5      20
Pier Skew, UpSta & Num, DnSta & Num=  ,404.98, 2 ,427.78, 2 , 0 , 0 , 0 ,,
    2.97    2.97
      -5      20
    2.97    2.97
      -5      20
Pier Skew, UpSta & Num, DnSta & Num=  ,455.88, 2 ,478.66, 2 , 0 , 0 , 0 ,,
     2.7     2.7
      -5      20
     2.7     2.7
      -5      20
Pier Skew, UpSta & Num, DnSta & Num=  ,506.88, 2 ,529.66, 2 , 0 , 0 , 0 ,,
    2.41    2.41
      -5      20
    2.41    2.41
      -5      20
BR Coef=-1 , 0 , 0 ,, 0 ,,,0.8,-1,,0,
WSPro=,,,, 1 ,,,, 0 ,,,, 0 ,,,,-1 ,-1 ,-1 , 0 , 0 , 0 , 0 , 0
BR U #Sta/Elev= 44
       0   17.26   12.98   12.39   27.84    8.14   48.09    7.78   69.88     7.9
   91.84    7.83  112.66     7.9  135.55     7.9  156.96    7.81  178.43    7.65
     199    7.69  203.01    7.17   207.4    6.39  211.42    5.77  218.91     2.7
  229.06    2.75  243.78    1.06  262.24     .89  278.06       0   291.9    -.65
  304.49    -.04  318.13    1.89  327.16    1.97  344.52    2.07  357.51    2.42
  374.28     1.7  385.06     .05  400.25    -.24  412.27    1.12  425.87    5.45
  427.42    6.37   432.1    7.01  437.69    7.74  457.24    7.43  476.77    7.13
   498.1    7.04  517.84    7.12  536.57    7.77  552.12    11.2  564.22   18.16
  574.11   22.41  588.18   23.35  609.46   23.25  633.37   23.11
BR U #Mann= 4
       0     .95   27.84    .035     199      .2  437.69    .035
BR U Banks=199,437.69
BR D #Sta/Elev= 49
       0   10.35      21    9.08   41.65     8.4   64.58    7.75   85.98    7.97
  106.38    8.07  125.87    8.33   145.7    8.71  168.11    9.27  192.29   10.09
  210.25    8.74  220.12    7.59  227.57     7.1  236.37    6.38  238.32     6.1
   245.7    4.92   254.2    2.68  263.47     .67  275.36     .81  288.97     .94
  304.74    1.89  322.23    3.58  341.07    4.31  362.87     3.7  363.01    3.72
  382.62    3.52  394.53    2.25  403.96      .8  419.02     .97  428.68    3.53
   440.6    6.16  441.37    6.38  448.17    6.98  459.02     7.5  475.81    8.31
  492.99    8.37  512.85    8.63  533.41    8.87  552.15    8.66  564.21    8.81
   573.9   10.85  583.12   13.93  589.65   18.13  596.63    22.1  607.62   23.11
  623.77   22.89  642.57   22.72   660.5   22.75  679.02    22.8
BR D #Mann= 3
       0      .5  210.25      .2  475.81     .95
BR D Banks=192.29,475.81
BC Design=,, 0 ,, 0 ,,,,,,
BC HTab HWMax=16.66
BC Use User HTab Curves=0
BC User HTab FreeFlow(D)= 0

Type RM Length L Ch R = 1 ,318.19  ,16.1745,16.1745,16.1745
BEGIN DESCRIPTION:
MFL_SR46A
END DESCRIPTION:
Node Name=MFL_SR46A
XS GIS Cut Line= 3
 458972.715004883187593.78647002459149.7894048793187585.95147002
459323.6393266723187578.25914331
#Sta/Elev= 30
       0   10.35      52    7.63      87    8.22     157    8.48     167    9.15
     184     9.3     207     8.9     227    7.42     247    4.76     257    2.16
     267     .76     286     .36     307    1.46     327    3.36     357    4.56
     377    3.76     387    1.96     397    1.16     417    1.16     427    2.71
     439    5.66     448    7.05  486.94   8.238     557    8.28  564.21    8.81
   573.9   10.85  583.12   13.93  596.63    22.1  607.62   23.11  679.02    22.8
#Mann= 3 , 0 , 0
       0     .22       0     184      .2       0  486.94     .22       0
Bank Sta=184,486.94
XS Rating Curve= 0 ,0
Exp/Cntr=0.5,0.3

Type RM Length L Ch R = 1 ,318.03  ,78.5761,78.5761,78.5761
BEGIN DESCRIPTION:
XS9
END DESCRIPTION:
Node Name=XS9
XS GIS Cut Line= 2
 458968.757504883187600.67747002459170.9561048793187586.74517002
#Sta/Elev= 30
       0   10.35      21    9.08   64.58    7.75  125.87    8.33  192.29   10.09
  236.37    6.38   245.7    4.92   254.2    2.68  263.47     .67  288.97     .94
  304.74    1.89  322.23    3.58  341.07    4.31  382.62    3.52  394.53    2.25
  403.96      .8  419.02     .97  428.68    3.53  441.37    6.38  448.17    6.98
  475.81    8.31  533.41    8.87  564.21    8.81   573.9   10.85  583.12   13.93
  589.65   18.13  596.63    22.1  607.62   23.11  642.57   22.72  679.02    22.8
#Mann= 3 , 0 , 0
       0     .22       0  192.29      .2       0  475.81     .22       0
Bank Sta=192.29,475.81
XS Rating Curve= 0 ,0
Exp/Cntr=0.5,0.3

Type RM Length L Ch R = 1 ,317.25  ,143.1102,143.1102,143.1102
BEGIN DESCRIPTION:
MFL_SR46F
END DESCRIPTION:
Node Name=MFL_SR46F
#Sta/Elev= 30
 -150.52    14.3   20.95     7.8  190.85    5.86  226.96    6.78     406    6.63
     417    5.04     422    3.54     427     .04     442   -3.66     447   -3.66
     452   -1.76     462    -.56     472    -.76     487     .74     507    4.64
     517    5.64     522    7.45     577    7.25     582    5.34     592    2.94
     607     .44     632    1.74     672    6.64   716.2     7.1  717.87    7.98
   763.1    6.66  817.89    7.07  878.48    9.23   897.8   10.27  905.78   11.67
#Mann= 3 , 0 , 0
 -150.52     .22       0     406      .2       0     522     .22       0
#XS Ineff= 1 ,-1
  157.53  206.53    6.67
Permanent Ineff=
       F
Bank Sta=406,522
XS Rating Curve= 0 ,0
Exp/Cntr=0.3,0.1

Type RM Length L Ch R = 1 ,315.81  ,997.3753,997.3753,997.3753
BEGIN DESCRIPTION:
XS8
XS8
END DESCRIPTION:
Node Name=XS8
XS GIS Cut Line= 2
 458917.374004883187636.49117002 459187.742604883187689.83957002
#Sta/Elev= 30
 -150.52    14.3       0    8.29   63.91    7.24  157.53    6.69  190.85    5.86
  206.53    6.67  325.03    6.67  365.22    7.06     366    7.63  421.89    -.44
  450.99     .06  477.02    2.51  490.39     5.5  494.86    7.36  527.01    6.67
  585.88    6.73  594.18    8.08  608.44    6.77   621.6    2.26  633.11    1.05
  673.47     2.5   684.5    2.05  698.82    3.28   716.2     7.1  717.87    7.98
  748.38    6.81   798.6    6.66  878.48    9.23   897.8   10.27  905.78   11.67
#Mann= 3 , 0 , 0
 -150.52     .22       0     366      .2       0  494.86     .22       0
#XS Ineff= 1 ,-1
  157.53  206.53    6.67
Permanent Ineff=
       F
Bank Sta=366,494.86
XS Rating Curve= 0 ,0
Exp/Cntr=0.3,0.1

Type RM Length L Ch R = 1 ,305.84  ,30.4134,30.4134,30.4134
BEGIN DESCRIPTION:
XS7
END DESCRIPTION:
Node Name=XS7
XS GIS Cut Line= 2
458912.9379048793188032.57667002 459199.229404883187905.09737002
#Sta/Elev= 30
       0   10.14  177.56    7.82  318.03    6.89  372.37    7.87  375.96    7.37
  378.14    4.98  399.46    3.24  420.29    4.03     457    3.46  507.07    4.16
   542.5     3.3  579.19    4.34  689.43     3.9  710.74    4.72  717.21    6.29
  733.55    7.32  741.28     6.3  743.89    3.82  775.54     .63  797.98    7.13
  805.16    7.82  810.18    6.94  876.64    6.23  891.82    2.76  902.61    1.94
  928.63    3.05  942.04    5.31  945.29    7.68  948.81    8.82 1032.06   11.73
#Mann= 5 , 0 , 0
       0     .22       0  177.56     .22       0  372.37      .2       0
  733.55     .22       0  805.16     .22       0
#XS Ineff= 1 ,-1
  805.16  945.29    7.82
Permanent Ineff=
       F
Bank Sta=372.37,733.55
XS Rating Curve= 0 ,0
Exp/Cntr=0.3,0.1

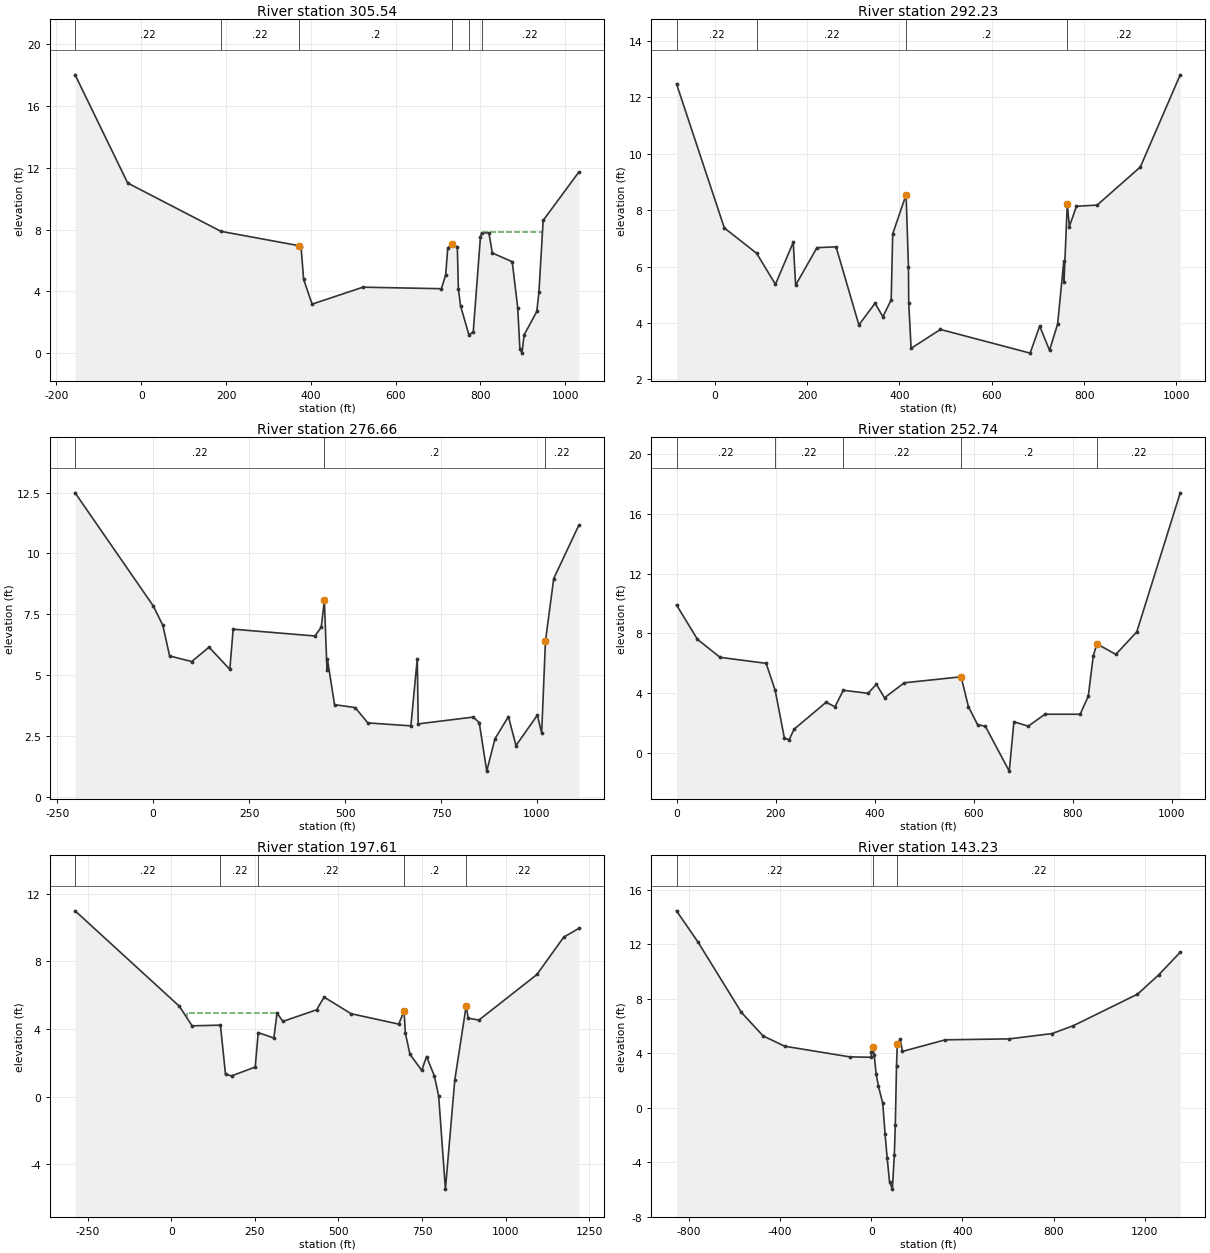
Type RM Length L Ch R = 1 ,305.54  ,1330.971,1330.971,1330.971
BEGIN DESCRIPTION:
MFL_Maple
END DESCRIPTION:
Node Name=MFL_Maple
XS GIS Cut Line= 4
458874.819588939 3188076.6633844 459012.990904883188004.24317002
459034.858588939 3187992.7815844459109.3117230033187953.75820322
#Sta/Elev= 30
    -156  18.031     -32  11.021     188   7.891  372.37    6.96     377   6.851
     383   4.774     403   3.174     523   4.274     708   4.174     718   5.074
     723   6.824  733.55   7.048   745.5   6.874     748   4.174     753   3.074
     773   1.174     783   1.374     800   7.521     803   7.794     820   7.794
     828   6.491     875   5.921     888   2.921     893    .271     898    .001
     903   1.181     933   2.701     938   3.971     948   8.601 1032.06   11.73
#Mann= 6 , 0 , 0
    -156     .22       0     188     .22       0  372.37      .2       0
  733.55     .22       0     773     .22       0     803     .22       0
#XS Ineff= 1 ,-1
  805.16  945.29    7.82
Permanent Ineff=
       F
Bank Sta=372.37,733.55
XS Rating Curve= 0 ,0
Exp/Cntr=0.3,0.1

Type RM Length L Ch R = 1 ,292.23  ,1556.693,1556.693,1556.693
BEGIN DESCRIPTION:
XS6
END DESCRIPTION:
Node Name=XS6
XS GIS Cut Line= 2
 459066.962404883188398.80067002 459329.354904883188309.45017002
#Sta/Elev= 30
  -82.59   12.48   20.95    7.37   90.95    6.47  131.64    5.37  170.22    6.86
  175.34    5.34  221.51    6.67  262.91     6.7  312.35    3.93  347.42     4.7
  364.26    4.22  382.29    4.82  385.58    7.16  414.57    8.55  419.68       6
  420.26    4.72  425.41     3.1  488.98    3.77  683.22    2.93  703.84    3.89
  725.17    3.03  742.68    3.96  756.14     6.2  756.48    5.44  763.62    8.22
  768.16    7.42  783.48    8.14  828.24    8.18   921.8    9.53 1008.19    12.8
#Mann= 4 , 0 , 0
  -82.59     .22       0   90.95     .22       0  414.57      .2       0
  763.62     .22       0
Bank Sta=414.57,763.62
XS Rating Curve= 0 ,0
Exp/Cntr=0.3,0.1

Type RM Length L Ch R = 1 ,276.66  ,2392.52,2392.52,2392.52
BEGIN DESCRIPTION:
XS5
END DESCRIPTION:
Node Name=XS5
XS GIS Cut Line= 2
459206.6051048793188905.35087002 459496.043504883188734.50867002
#Sta/Elev= 30
 -203.47   12.49       0    7.85   25.07    7.05   42.91    5.79  100.41    5.56
  145.54    6.15   199.7    5.24  208.46    6.89  421.34    6.61  438.02    6.97
  446.08    8.07  452.93    5.22  453.93    5.67  472.65    3.79   526.4    3.67
   559.4    3.04  671.59    2.92  688.24    5.68  690.71       3  834.22    3.28
   849.8    3.05  869.25    1.06  890.73    2.39  925.72     3.3  945.46    2.11
 1001.21    3.36 1012.38    2.62 1022.29    6.41 1043.84    8.97 1109.23   11.16
#Mann= 3 , 0 , 0
 -203.47     .22       0  446.08      .2       0 1022.29     .22       0
Bank Sta=446.08,1022.29
XS Rating Curve= 0 ,0
Exp/Cntr=0.3,0.1

Type RM Length L Ch R = 1 ,252.74  ,5512.566,5512.566,5512.566
BEGIN DESCRIPTION:
XS4
END DESCRIPTION:
Node Name=XS4
XS GIS Cut Line= 2
 459796.085804883189458.56807002459959.3749048793189243.81887002
#Sta/Elev= 30
       0     9.9   42.39     7.6   88.08     6.4  181.08       6  199.29     4.2
  217.94       1  227.49      .9  237.53     1.6  302.16     3.4  320.12     3.1
  336.83     4.2  386.81       4  403.81     4.6  420.13     3.7  459.91     4.7
  574.87     5.1  589.66     3.1  608.16     1.9   623.7     1.8  672.08    -1.2
  681.48     2.1  710.32     1.8  744.17     2.6  815.27     2.6  831.64     3.8
  841.78     6.5  848.97     7.3  887.35     6.6  929.63     8.1 1017.41   17.39
#Mann= 5 , 0 , 0
       0     .22       0  199.29     .22       0  336.83     .22       0
  574.87      .2       0  848.97     .22       0
Bank Sta=574.87,848.97
XS Rating Curve= 0 ,0
Exp/Cntr=0.3,0.1

Type RM Length L Ch R = 1 ,197.61  ,5438.025,5438.025,5438.025
BEGIN DESCRIPTION:
XS3
END DESCRIPTION:
Node Name=XS3
XS GIS Cut Line= 2
460829.9461048793190407.87167002 461055.296404883190115.14967002
#Sta/Elev= 30
 -287.57      11   24.29    5.35   62.45    4.19  147.14    4.23  162.34    1.31
  181.07    1.23  251.16    1.75  260.17    3.79  306.92    3.47  316.45    4.95
  333.84    4.45  434.75    5.14  457.35    5.89  537.66    4.91  680.61    4.29
  696.41    5.08  700.12    3.78  713.88    2.51  749.25    1.55  763.67    2.37
  786.91    1.23  799.86     .04  820.09   -5.48  848.03     .97  882.09    5.36
   888.3    4.64   920.2    4.53 1093.85    7.23 1173.86    9.44 1219.12    9.96
#Mann= 5 , 0 , 0
 -287.57     .22       0  147.14     .22       0  260.17     .22       0
  696.41      .2       0  882.09     .22       0
#XS Ineff= 1 ,-1
   48.35  316.45    4.95
Permanent Ineff=
       T
Bank Sta=696.41,882.09
XS Rating Curve= 0 ,0
Exp/Cntr=0.3,0.1

Type RM Length L Ch R = 1 ,143.23  ,6633.826,6633.826,6633.826
BEGIN DESCRIPTION:
XS2
END DESCRIPTION:
Node Name=XS2
XS GIS Cut Line= 2
461765.1722048793191043.89447002461806.0515048793191038.38137002
#Sta/Elev= 30
 -855.27   14.47 -760.24   12.16 -570.18    7.01 -475.15    5.29 -380.12    4.53
  -95.03    3.75       0    3.72     .19    4.13       7    4.48   12.81    3.86
   21.53    2.47    31.3    1.59    50.2     .35   60.36   -1.88   69.85   -3.71
   80.05   -5.43   92.54   -5.96  101.09   -3.44  105.43   -1.23  110.62    3.06
   113.9    4.68   126.9    5.03  136.82    4.15  324.44       5  605.87    5.07
  793.49    5.46   887.3    6.04 1168.73    8.35 1262.54    9.78 1356.34   11.43
#Mann= 3 , 0 , 0
 -855.27     .22       0       7      .2       0   113.9     .22       0
#XS Ineff= 1 ,-1
 -380.12       7    4.48
Permanent Ineff=
       T
Bank Sta=7,113.9
XS Rating Curve= 0 ,0
Exp/Cntr=0.3,0.1

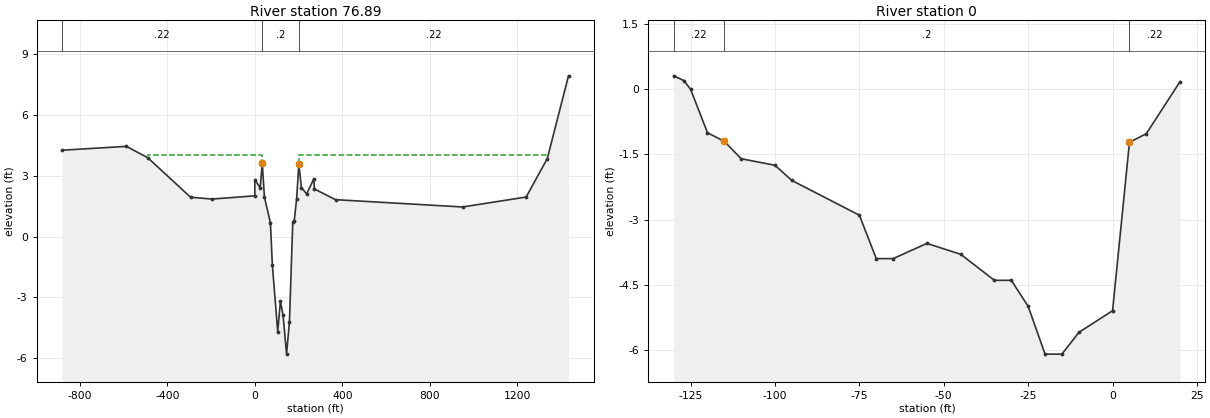
Type RM Length L Ch R = 1 ,76.89   ,2563,2563,2563
BEGIN DESCRIPTION:
XS1
END DESCRIPTION:
Node Name=XS1
XS GIS Cut Line= 2
 462803.448104883191969.26997002 462859.554904883191908.91657002
#Sta/Elev= 30
 -880.67    4.26 -587.12    4.45 -489.26    3.89 -293.56    1.94 -195.71    1.85
       0    2.01     .13     2.8   24.53    2.41   33.99    3.61   43.96    1.95
   71.39     .67   80.11   -1.39  104.67   -4.69  117.04    -3.2  129.29   -3.88
  145.01    -5.8  158.26   -4.21  173.58     .72  179.97     .75  191.04    1.85
  201.37    3.56  212.86    2.42  236.92     2.1  270.18    2.86  272.17    2.35
  368.96    1.82  949.73    1.46 1240.11    1.95 1336.91    3.85  1433.7    7.93
#Mann= 3 , 0 , 0
 -880.67     .22       0   33.99      .2       0  201.37     .22       0
#XS Ineff= 2 ,-1
 -489.26   33.99       4  201.37 1336.91       4
Permanent Ineff=
       F       F
Bank Sta=33.99,201.37
XS Rating Curve= 0 ,0
Exp/Cntr=0.3,0.1

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
Type RM Length L Ch R = 1 ,0       ,7.0538,7.0538,7.0538
BEGIN DESCRIPTION:
LoWek
END DESCRIPTION:
Node Name=LoWek
XS GIS Cut Line= 2
  463445.2442725 3193619.5738227  463552.4459684 3193623.8064514
#Sta/Elev= 23
    -130    .312    -127    .202    -125    .002    -120   -.998    -115  -1.198
    -110  -1.598    -100  -1.748     -95  -2.098     -75  -2.898     -70  -3.898
     -65  -3.898     -55  -3.548     -45  -3.798     -35  -4.398     -30  -4.398
     -25  -4.998     -20  -6.098     -15  -6.098     -10  -5.598       0  -5.098
       5   -1.22      10   -1.02      20     .18
#Mann= 3 , 0 , 0
    -130     .22       0    -115      .2       0       5     .22       0
Bank Sta=-115,5
XS Rating Curve= 0 ,0
Exp/Cntr=0.3,0.1
Stream Node=LtWekiva        ,LtWekiva        , 0 , 0 ,Upstream end
Stream Node=LtWekiva        ,LtWekiva        , 0 , 1 ,Downstream end
Stream Node=ROK             ,ROK             , 0 , 0 ,Upstream end
Stream Node=ROK             ,ROK             , 0 , 1 ,Downstream end
Stream Node=wekiva          ,wek_run         , 0 , 0 ,Upstream end
Stream Node=wekiva          ,wek_run         , 0 , 1 ,Downstream end
Stream Node=wekiva          ,wekiva_riv_up   , 0 , 0 ,Upstream end
Stream Node=wekiva          ,wekiva_riv_up   , 0 , 1 ,Downstream end
Stream Node=wekiva          ,wekiva_riv_down , 0 , 0 ,Upstream end
Stream Node=wekiva          ,wekiva_riv_down , 0 , 1 ,Downstream end
LCMann Table=0