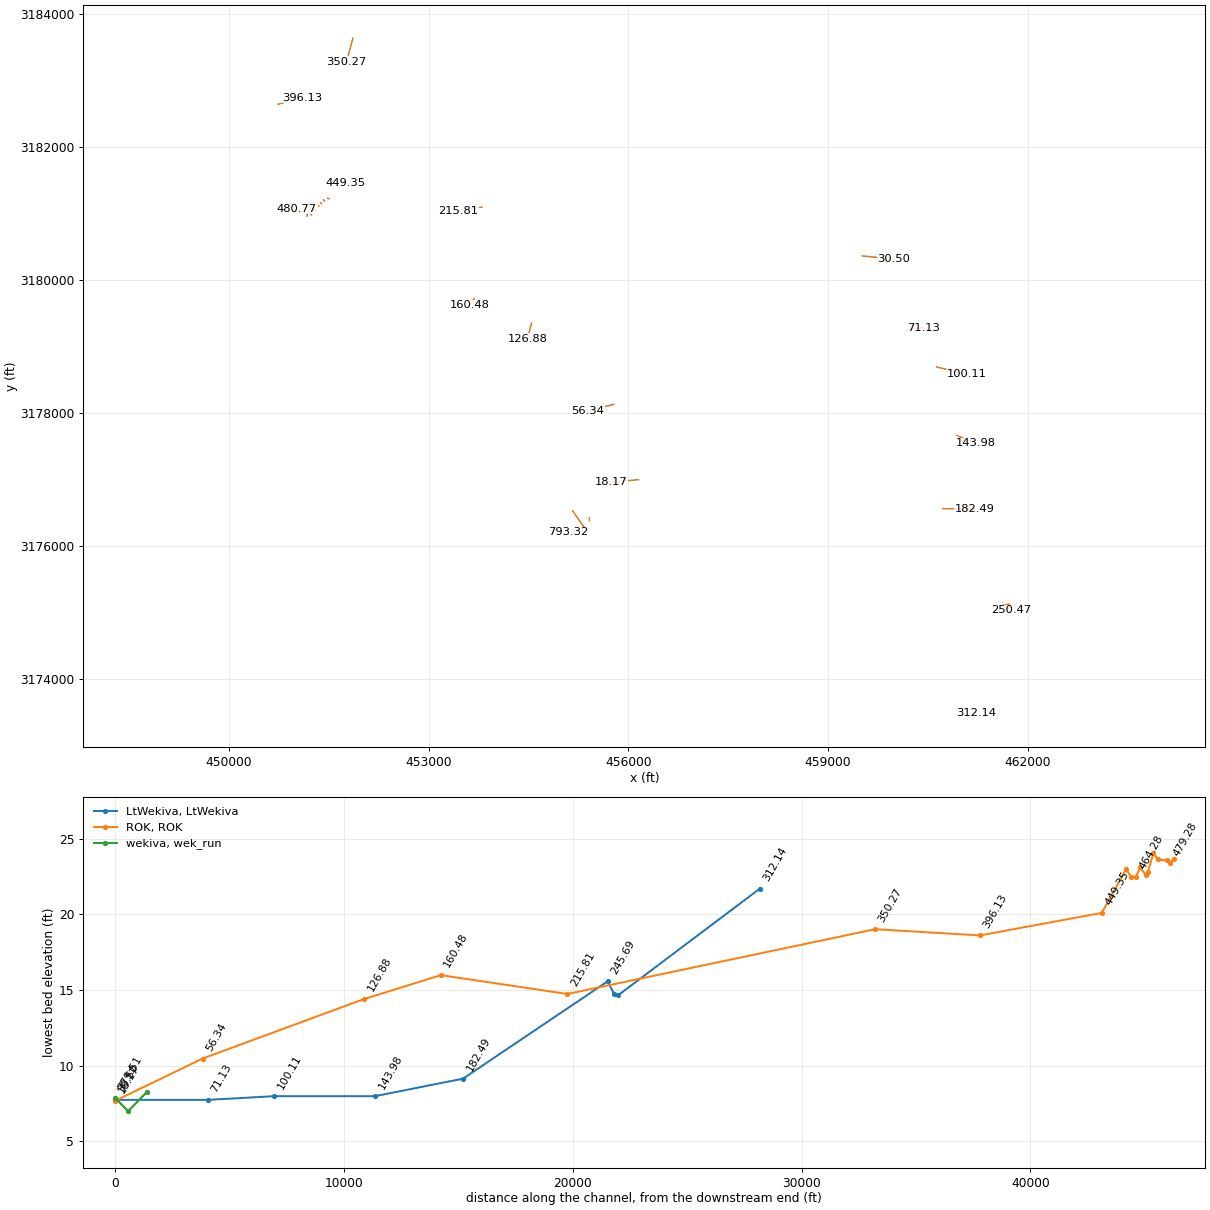
HEC-RAS study wekiva_ras.prj: wekiva_ras

--- wekiva_ras.g01 (geometry) --- (continued)

Chan Stop Cuts=-1
Use User Specified Reach Order=0
Roughness Change=ROK             ,ROK             ,160.48  ,18.17   , 5
      50       1      60     .85      75      .7     120      .6     420      .5
Roughness Change=wekiva          ,wekiva_riv_down ,544.57  ,0       , 5
     140       1     200      .8     400     .65     700    .575    2000      .5
Roughness Change=ROK             ,ROK             ,215.81  ,215.81  , 5
      48       1      51     .85      55      .7      60      .6     250      .5
Roughness Change=ROK             ,ROK             ,396.13  ,350.27  , 5
      46       1      49     .85      51      .7      54      .6     120      .5
Roughness Change=LtWekiva        ,LtWekiva        ,100.11  ,30.50   , 5
      30       1      50    .773      70    .636     140    .545    1020    .455
Roughness Change=LtWekiva        ,LtWekiva        ,143.98  ,143.98  , 5
      30       1      48    .773      70    .636     120    .545     640    .455
Roughness Change=wekiva          ,wekiva_riv_up   ,678.62  ,579.64  , 5
     110       1     130      .8     250     .65     550    .575    1000      .5
Composite Channel Slope=5

--- wekiva_ras.g05 (geometry) ---

Geom Title=wekiva_ras_2018_ft_3
Program Version=5.03

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
River Reach=LtWekiva        ,LtWekiva

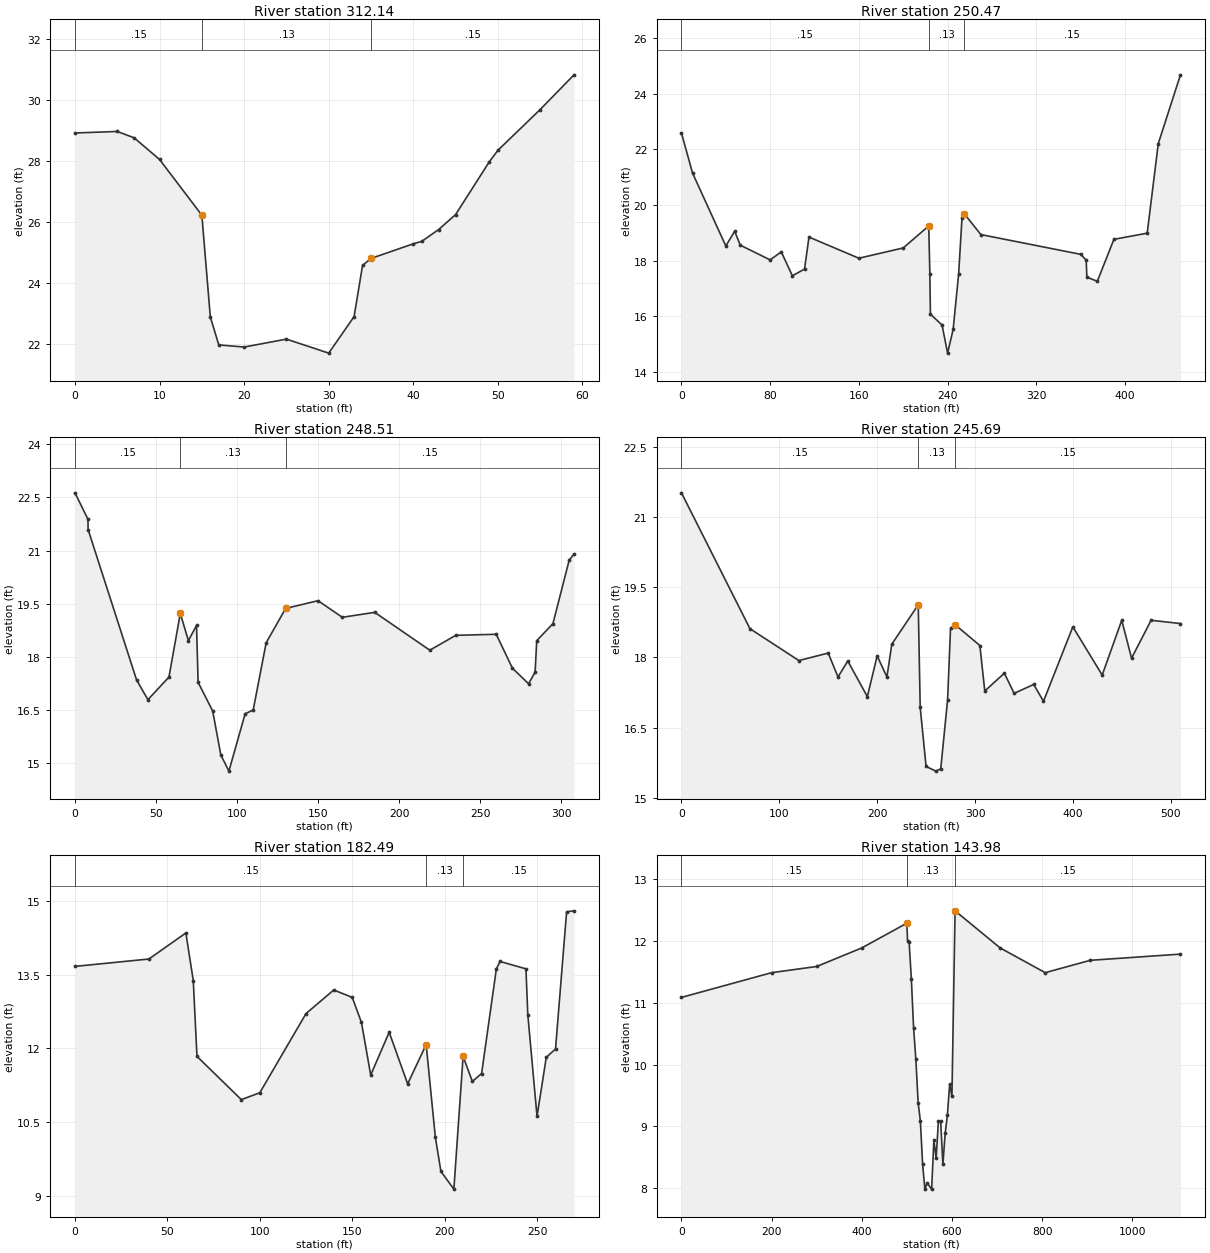
Type RM Length L Ch R = 1 ,312.14  ,6167.191,6167.191,6167.191
BEGIN DESCRIPTION:
TheSprings
END DESCRIPTION:
Node Name=TheSprings
XS GIS Cut Line= 2
461204.5570048793173492.65727002461225.0887048793173489.69387002
#Sta/Elev= 21
       0   28.92       5   28.97       7   28.76      10   28.05      15   26.22
      16   22.88      17   21.96      20   21.89      25   22.15      30   21.69
      33   22.89      34   24.57      35    24.8      40   25.28      41   25.36
      43   25.75      45   26.24      49   27.98      50   28.35      55   29.69
      59   30.83
#Mann= 3 , 0 , 0
       0     .15       0      15     .13       0      35     .15       0
Bank Sta=15,35
XS Rating Curve= 0 ,0
Exp/Cntr=0.3,0.1

Type RM Length L Ch R = 1 ,250.47  ,195.8661,195.8661,195.8661
BEGIN DESCRIPTION:
MFL_SLB_south
END DESCRIPTION:
Node Name=MFL_SLB_south
XS GIS Cut Line= 2
 461695.722804883174963.91247002461744.7818048793175039.17377002
#Sta/Elev= 30
       0  22.582      10  21.142      40  18.522      48  19.052      53  18.552
      80  18.022      90  18.312     100  17.452     111  17.692     115  18.842
     160  18.082     200  18.452     223  19.242     224  17.512   224.5  16.072
     235  15.682     240  14.672     245  15.522     250  17.532     253  19.542
     255  19.682     270  18.932     360  18.222     365  18.012   365.6  17.402
     375  17.252     390  18.762     420  18.982     430  22.202     450  24.672
#Mann= 3 , 0 , 0
       0     .15       0     223     .13       0     255     .15       0
Bank Sta=223,255
XS Rating Curve= 0 ,0
Exp/Cntr=0.3,0.1

Type RM Length L Ch R = 1 ,248.51  ,282.3819,282.3819,282.3819
BEGIN DESCRIPTION:
MFL_SLB_bridge
END DESCRIPTION:
Node Name=MFL_SLB_bridge
XS GIS Cut Line= 2
461657.0487048793175034.72957002461736.0472048793175081.44547002
#Sta/Elev= 30
       0  22.632       8  21.882     8.1  21.592      38  17.342      45  16.782
      58  17.422      65  19.222      70  18.452      75  18.882      76  17.272
      85  16.462      90  15.222      95  14.762     105  16.382     110  16.492
     118  18.392     130  19.362     150  19.582     165  19.112     185  19.252
     219  18.182     235  18.602     260  18.632     270  17.672     280  17.232
     284  17.562     285  18.452     295  18.932     305  20.722     308  20.902
#Mann= 3 , 0 , 0
       0     .15       0      65     .13       0     130     .15       0
Bank Sta=65,130
XS Rating Curve= 0 ,0
Exp/Cntr=0.3,0.1

Type RM Length L Ch R = 1 ,245.69  ,6319.948,6319.948,6319.948
BEGIN DESCRIPTION:
MFL_SLB_north
END DESCRIPTION:
Node Name=MFL_SLB_north
XS GIS Cut Line= 2
461616.7210048793175109.23877002 461714.682104883175129.98127002
#Sta/Elev= 30
       0  21.512      70  18.612     120  17.932     150  18.092     160  17.582
     170  17.922     190  17.162     200  18.032     210  17.582     215  18.282
     242  19.122     244  16.932     250  15.672     260  15.572     265  15.622
     272  17.092     275  18.622     280  18.692     305  18.252     310  17.282
     330  17.662     340  17.232     360  17.422     370  17.062     400  18.652
     430  17.622     450  18.792     460  17.982     480  18.792     510  18.722
#Mann= 3 , 0 , 0
       0     .15       0     242     .13       0     280     .15       0
Bank Sta=242,280
XS Rating Curve= 0 ,0
Exp/Cntr=0.3,0.1

Type RM Length L Ch R = 1 ,182.49  ,3850.361,3850.361,3850.361
BEGIN DESCRIPTION:
MFL_Sabol
MFL_Sabol
END DESCRIPTION:
Node Name=MFL_Sabol
XS GIS Cut Line= 2
 460724.291904883176565.62067002 461198.426104883176557.15397002
#Sta/Elev= 30
       0  13.668      40  13.818      60  14.348      64  13.378      66  11.838
      90  10.958     100  11.098     125  12.708     140  13.188     150  13.038
     155  12.528     160  11.458     170  12.328     180  11.278     190  12.078
     195  10.188     198   9.498     205   9.138     210  11.838     215  11.328
     220  11.488     228  13.618     230  13.768     244  13.618     245  12.688
     250  10.618     255  11.818     260  11.988     266  14.778     270  14.798
#Mann= 3 , 0 , 0
       0     .15       0     190     .13       0     210     .15       0
Bank Sta=190,210
XS Rating Curve= 0 ,0
Exp/Cntr=0.3,0.1

Type RM Length L Ch R = 1 ,143.98  ,4387.369,4387.369,4387.369
BEGIN DESCRIPTION:
LW2
END DESCRIPTION:
Node Name=LW2
XS GIS Cut Line= 2
 460933.299004883177665.03007002461212.6995048793177544.37987002
#Sta/Elev= 30
       0  11.086     200  11.486     300  11.586     400  11.886     500  12.286
   501.5  12.006     505  11.986     510  11.386     515  10.586     520  10.086
     525   9.386     530   9.086     535   8.386     540   7.986     545   8.086
     555   7.986     560   8.786     565   8.486     570   9.086     575   9.086
     580   8.386     585   8.886     590   9.186     595   9.686     600   9.486
     607  12.486     707  11.886     807  11.486     907  11.686    1107  11.786
#Mann= 3 , 0 , 0
       0     .15       0     500     .13       0     607     .15       0
Bank Sta=500,607
XS Rating Curve= 0 ,0
Exp/Cntr=0.3,0.1

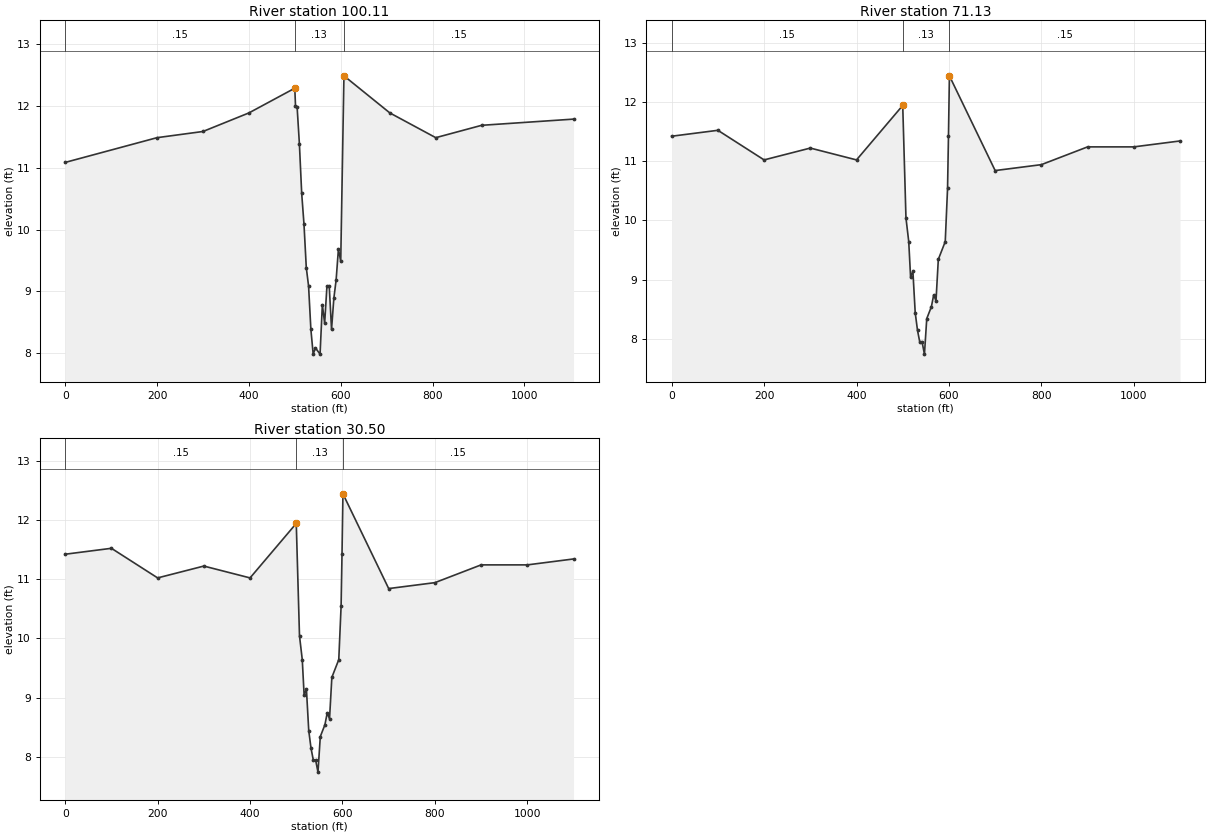
Type RM Length L Ch R = 1 ,100.11  ,2898.097,2898.097,2898.097
BEGIN DESCRIPTION:
WK19
END DESCRIPTION:
Node Name=WK19
XS GIS Cut Line= 2
 460629.076904883178693.61577002461086.2779048793178583.54887002
#Sta/Elev= 30
       0  11.086     200  11.486     300  11.586     400  11.886     500  12.286
   501.5  12.006     505  11.986     510  11.386     515  10.586     520  10.086
     525   9.386     530   9.086     535   8.386     540   7.986     545   8.086
     555   7.986     560   8.786     565   8.486     570   9.086     575   9.086
     580   8.386     585   8.886     590   9.186     595   9.686     600   9.486
     607  12.486     707  11.886     807  11.486     907  11.686    1107  11.786
#Mann= 3 , 0 , 0
       0     .15       0     500     .13       0     607     .15       0
Bank Sta=500,607
XS Rating Curve= 0 ,0
Exp/Cntr=0.3,0.1

Type RM Length L Ch R = 1 ,71.13   ,4063.156,4063.156,4063.156
BEGIN DESCRIPTION:
LW1
END DESCRIPTION:
Node Name=LW1
XS GIS Cut Line= 2
460177.6475048793179246.18327002 460425.298004883179284.28337002
#Sta/Elev= 29
       0  11.422     100  11.522     200  11.022     300  11.222     400  11.022
     500  11.942     507  10.042     513   9.642     517   9.042     522   9.142
     527   8.442     532   8.142     537   7.942     542   7.942     547   7.742
     552   8.342     562   8.542     567   8.742     572   8.642     577   9.342
     592   9.642     597  10.542     599  11.432     601  12.442     700  10.842
     800  10.942     900  11.242    1000  11.242    1100  11.342
#Mann= 3 , 0 , 0
       0     .15       0     500     .13       0     601     .15       0
Bank Sta=500,601
XS Rating Curve= 0 ,0
Exp/Cntr=0.3,0.1

Type RM Length L Ch R = 1 ,30.50   ,3049.836,3049.836,3049.836
BEGIN DESCRIPTION:
WK18
END DESCRIPTION:
Node Name=WK18
XS GIS Cut Line= 2
 459515.919704883180360.70577002 459987.937304883180315.19737002
#Sta/Elev= 29
       0  11.422     100  11.522     200  11.022     300  11.222     400  11.022
     500  11.942     507  10.042     513   9.642     517   9.042     522   9.142
     527   8.442     532   8.142     537   7.942     542   7.942     547   7.742
     552   8.342     562   8.542     567   8.742     572   8.642     577   9.342
     592   9.642     597  10.542     599  11.432     601  12.442     700  10.842
     800  10.942     900  11.242    1000  11.242    1100  11.342
#Mann= 3 , 0 , 0
       0     .15       0     500     .13       0     601     .15       0
Bank Sta=500,601
XS Rating Curve= 0 ,0
Exp/Cntr=0.3,0.1

River Reach=ROK             ,ROK

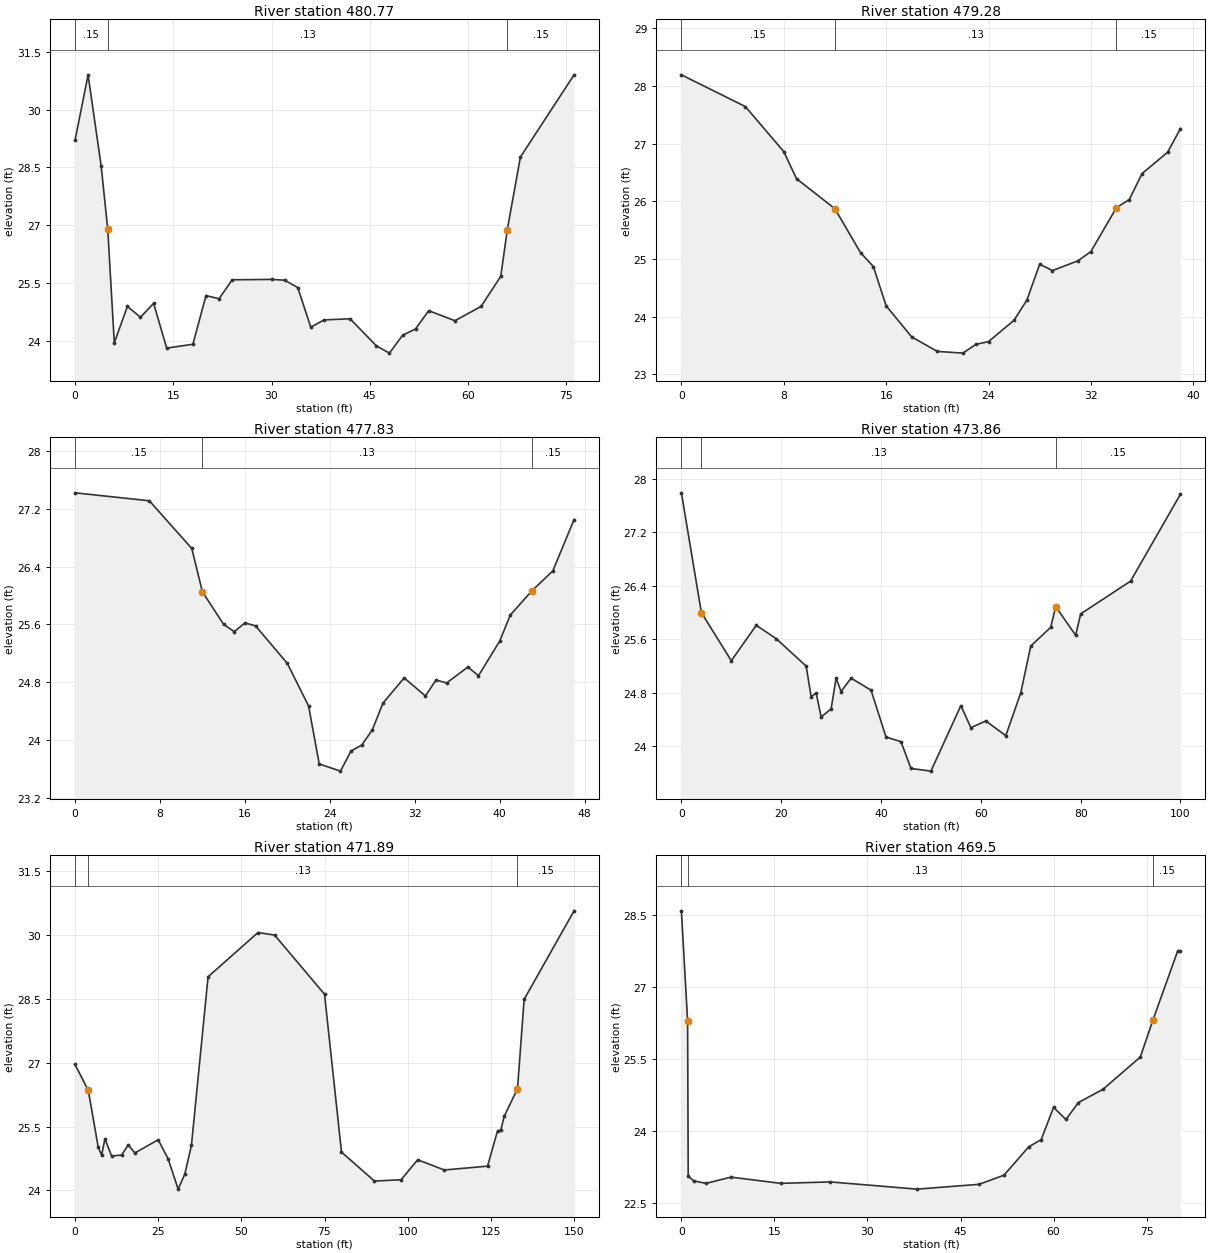
Type RM Length L Ch R = 1 ,480.77  ,149.0814,149.0814,149.0814
BEGIN DESCRIPTION:
RokSpr02
END DESCRIPTION:
Node Name=RokSpr02
XS GIS Cut Line= 2
451026.6781048793181095.07657002451022.5373048793181071.37427002
#Sta/Elev= 30
       0    29.2       2    30.9       4   28.53       5    26.9       6   23.96
       8    24.9      10   24.62      12   24.98      14   23.82      18   23.92
      20   25.18      22    25.1      24   25.59      30    25.6      32   25.58
      34   25.39      36   24.36      38   24.55      42   24.58      46   23.88
      48   23.69      50   24.15      52   24.32      54   24.79      58   24.53
      62    24.9      65   25.68      66   26.89      68   28.77   76.19    30.9
#Mann= 3 , 0 , 0
       0     .15       0       5     .13       0      66     .15       0
Bank Sta=5,66
XS Rating Curve= 0 ,0
Exp/Cntr=0.3,0.1

Type RM Length L Ch R = 1 ,479.28  ,145.1115,145.1115,145.1115
BEGIN DESCRIPTION:
RokSpr03
END DESCRIPTION:
Node Name=RokSpr03
XS GIS Cut Line= 2
451082.3677048793181066.28987002451051.4643048793181054.43647002
#Sta/Elev= 24
       0   28.19       5   27.64       8   26.86       9   26.39      12   25.87
      14   25.11      15   24.87      16   24.19      18   23.65      20    23.4
      22   23.37      23   23.52      24   23.57      26   23.94      27   24.29
      28   24.91      29    24.8      31   24.97      32   25.13      34   25.89
      35   26.03      36   26.48      38   26.85      39   27.26
#Mann= 3 , 0 , 0
       0     .15       0      12     .13       0      34     .15       0
Bank Sta=12,34
XS Rating Curve= 0 ,0
Exp/Cntr=0.3,0.1

Type RM Length L Ch R = 1 ,477.83  ,396.8176,396.8176,396.8176
BEGIN DESCRIPTION:
RokSpr04
END DESCRIPTION:
Node Name=RokSpr04
XS GIS Cut Line= 2
 451097.184404883181024.59137002 451068.609404883181013.79637002
#Sta/Elev= 27
       0   27.42       7   27.31      11   26.65      12   26.05      14    25.6
      15    25.5      16   25.62      17   25.58      20   25.06      22   24.47
      23   23.67      25   23.57      26   23.85      27   23.93      28   24.14
      29   24.51      31   24.86      33   24.61      34   24.83      35   24.79
      37   25.01      38   24.89      40   25.37      41   25.73      43   26.06
      45   26.34      47   27.05
#Mann= 3 , 0 , 0
       0     .15       0      12     .13       0      43     .15       0
Bank Sta=12,43
XS Rating Curve= 0 ,0
Exp/Cntr=0.3,0.1

Type RM Length L Ch R = 1 ,473.86  ,196.8176,196.8176,196.8176
BEGIN DESCRIPTION:
RokSpr05
END DESCRIPTION:
Node Name=RokSpr05
XS GIS Cut Line= 2
451175.4950048793180987.69237002451172.3109048793180957.39027002
#Sta/Elev= 30
       0   27.79       4      26      10   25.28      15   25.81      19   25.61
      25    25.2      26   24.74      27    24.8      28   24.44      30   24.56
      31   25.02      32   24.82      34   25.02      38   24.84      41   24.14
      44   24.07      46   23.67      50   23.63      56   24.61      58   24.28
      61   24.38      65   24.16      68    24.8      70    25.5      74   25.78
      75   26.09      79   25.66      80   25.98      90   26.47     100   27.77
#Mann= 3 , 0 , 0
       0     .15       0       4     .13       0      75     .15       0
Bank Sta=4,75
XS Rating Curve= 0 ,0
Exp/Cntr=0.3,0.1

Type RM Length L Ch R = 1 ,471.89  ,239.5013,239.5013,239.5013
BEGIN DESCRIPTION:
RokSpr06
END DESCRIPTION:
Node Name=RokSpr06
XS GIS Cut Line= 2
 451208.740504883181010.67257002451240.8860048793180978.17977002
#Sta/Elev= 30
       0   26.96       4   26.35       7   25.01       8   24.83       9   25.21
      11   24.81      14   24.83      16   25.07      18   24.88      25   25.19
      28   24.74      31   24.03      33   24.38      35   25.06      40   29.02
      55   30.06      60      30      75   28.61    80.1    24.9      90   24.22
      98   24.25     103   24.72     111   24.48     124   24.57     127    25.4
     128   25.42     129   25.74     133   26.39     135   28.49     150   30.57
#Mann= 3 , 0 , 0
       0     .15       0       4     .13       0     133     .15       0
Bank Sta=4,133
XS Rating Curve= 0 ,0
Exp/Cntr=0.3,0.1

Type RM Length L Ch R = 1 ,469.5   ,86.1877,86.1877,86.1877
BEGIN DESCRIPTION:
RokSpr08
END DESCRIPTION:
Node Name=RokSpr08
XS GIS Cut Line= 2
 451256.572004883181058.88917002451286.3376048793181034.67977002
#Sta/Elev= 21
       0   28.58       1   26.29     1.1   23.06       2   22.96       4   22.91
       8   23.04      16   22.91      24   22.94      38   22.79      48   22.89
      52   23.08      56   23.67      58   23.82      60   24.49      62   24.24
      64   24.59      68   24.87      74   25.54      76    26.3      80   27.74
   80.46   27.74
#Mann= 3 , 0 , 0
       0     .15       0       1     .13       0      76     .15       0
Bank Sta=1,76
XS Rating Curve= 0 ,0
Exp/Cntr=0.3,0.1

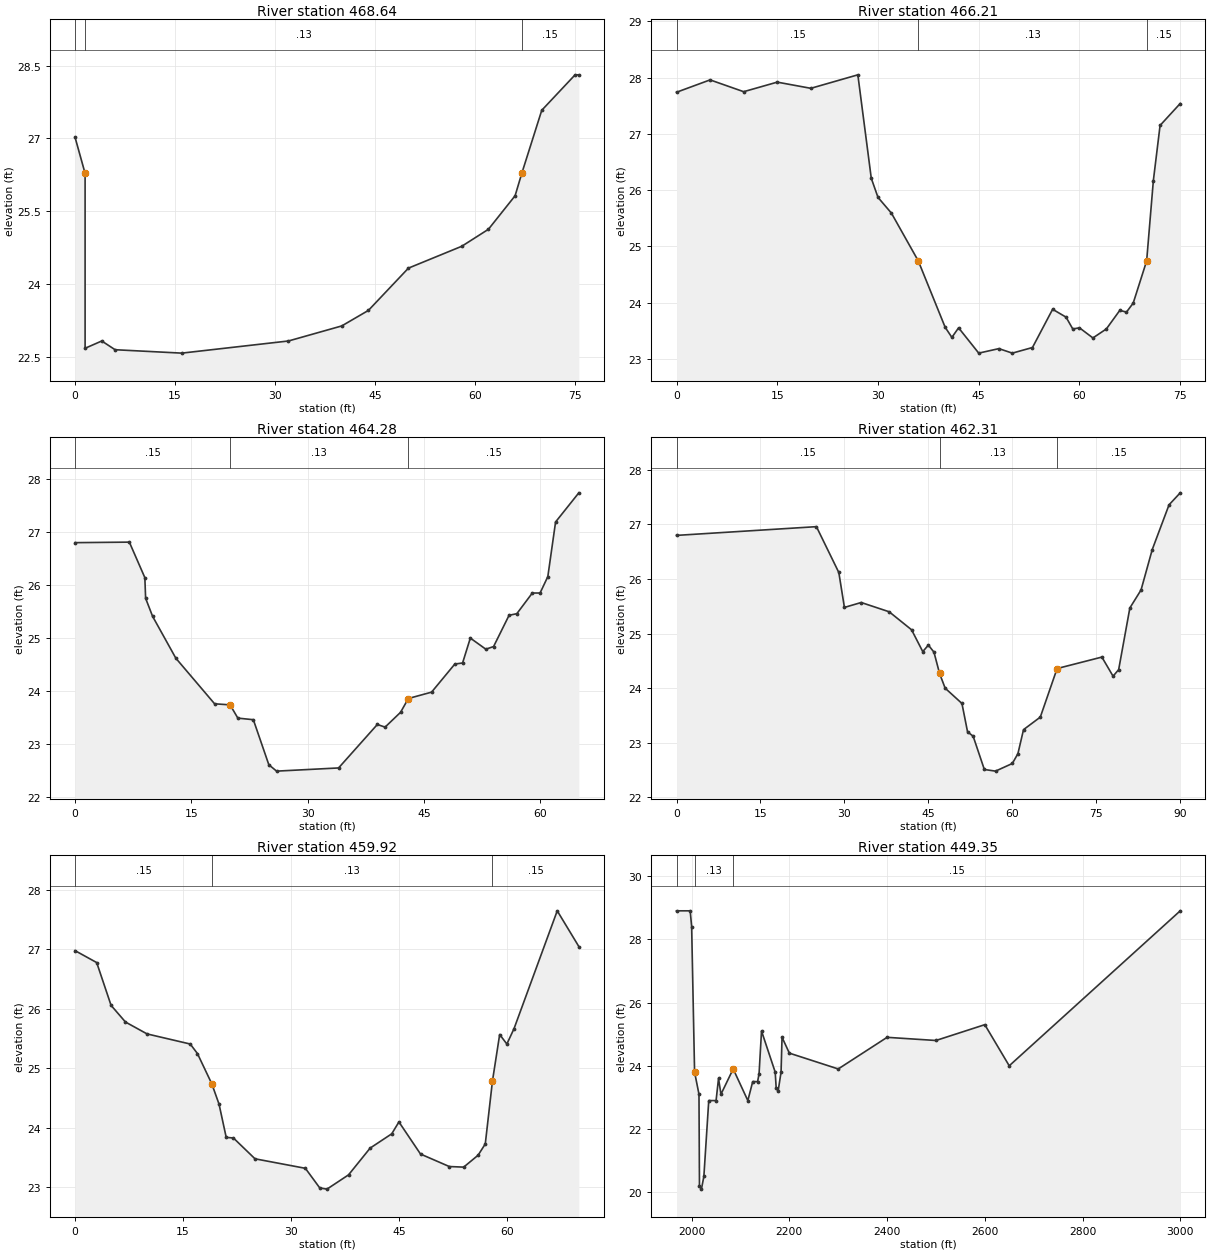
Type RM Length L Ch R = 1 ,468.64  ,242.6181,242.6181,242.6181
BEGIN DESCRIPTION:
RokSpr09
END DESCRIPTION:
Node Name=RokSpr09
XS GIS Cut Line= 2
 451276.415704883181079.12987002 451298.510204883181052.33677002
#Sta/Elev= 17
       0   27.02     1.5   26.28     1.5   22.68       4   22.83       6   22.65
      16   22.58      32   22.83      40   23.14      44   23.46      50   24.33
      58   24.78      62   25.13      66   25.82      67   26.28      70   27.58
      75   28.31   75.56   28.31
#Mann= 3 , 0 , 0
       0     .15       0     1.5     .13       0      67     .15       0
Bank Sta=1.5,67
XS Rating Curve= 0 ,0
Exp/Cntr=0.3,0.1

Type RM Length L Ch R = 1 ,466.21  ,193.2415,193.2415,193.2415
BEGIN DESCRIPTION:
RokSpr11
END DESCRIPTION:
Node Name=RokSpr11
XS GIS Cut Line= 2
451331.5027048793181121.98737002 451349.007504883181107.29797002
#Sta/Elev= 30
       0   27.74       5   27.96      10   27.75      15   27.92      20   27.81
      27   28.05      29   26.21      30   25.87      32   25.59      36   24.74
      40   23.56      41   23.38      42   23.55      45    23.1      48   23.18
      50    23.1      53    23.2      56   23.88      58   23.74      59   23.53
      60   23.55      62   23.37      64   23.53      66   23.86      67   23.83
      68   23.99      70   24.74      71   26.17      72   27.15      75   27.54
#Mann= 3 , 0 , 0
       0     .15       0      36     .13       0      70     .15       0
Bank Sta=36,70
XS Rating Curve= 0 ,0
Exp/Cntr=0.3,0.1

Type RM Length L Ch R = 1 ,464.28  ,196.4567,196.4567,196.4567
BEGIN DESCRIPTION:
RokSpr12
END DESCRIPTION:
Node Name=RokSpr12
XS GIS Cut Line= 2
 451376.887304883181161.36027002 451390.891104883181147.35337002
#Sta/Elev= 30
       0    26.8       7   26.81       9   26.14     9.1   25.75      10   25.41
      13   24.62      18   23.76      20   23.74      21   23.49      23   23.46
      25   22.61      26   22.49      34   22.55      39   23.37      40   23.32
      42    23.6      43   23.86      46   23.98      49   24.51      50   24.53
      51      25      53   24.79      54   24.84      56   25.43      57   25.46
      59   25.85      60   25.85      61   26.16      62   27.19      65   27.74
#Mann= 3 , 0 , 0
       0     .15       0      20     .13       0      43     .15       0
Bank Sta=20,43
XS Rating Curve= 0 ,0
Exp/Cntr=0.3,0.1

Type RM Length L Ch R = 1 ,462.31  ,239.5341,239.5341,239.5341
BEGIN DESCRIPTION:
RokSpr13
END DESCRIPTION:
Node Name=RokSpr13
XS GIS Cut Line= 2
451422.9117048793181205.33417002 451436.623104883181181.58607002
#Sta/Elev= 30
       0    26.8      25   26.96      29   26.12      30   25.48      33   25.57
      38    25.4      42   25.07      44   24.67      45   24.79      46   24.66
      47   24.27      48      24      51   23.72      52    23.2      53   23.12
      55   22.51      57   22.48      60   22.62      61    22.8      62   23.24
      65   23.47      68   24.36      76   24.57      78   24.22      79   24.34
      81   25.47      83    25.8      85   26.54      88   27.36      90   27.58
#Mann= 3 , 0 , 0
       0     .15       0      47     .13       0      68     .15       0
Bank Sta=47,68
XS Rating Curve= 0 ,0
Exp/Cntr=0.3,0.1

Type RM Length L Ch R = 1 ,459.92  ,1057.185,1057.185,1057.185
BEGIN DESCRIPTION:
RokSpr14
END DESCRIPTION:
Node Name=RokSpr14
XS GIS Cut Line= 2
451484.9297048793181229.40207002 451504.259604883181220.38617002
#Sta/Elev= 30
       0   26.98       3   26.78       5   26.06       7   25.78      10   25.58
      16   25.41      17   25.25      19   24.74      20    24.4      21   23.84
      22   23.83      25   23.48      32   23.32      34   22.99      35   22.97
      38   23.21      41   23.66      44    23.9      45    24.1      48   23.56
      52   23.35      54   23.34      56   23.54      57   23.73      58   24.79
      59   25.57      60   25.41      61   25.67      67   27.65      70   27.05
#Mann= 3 , 0 , 0
       0     .15       0      19     .13       0      58     .15       0
Bank Sta=19,58
XS Rating Curve= 0 ,0
Exp/Cntr=0.3,0.1

Type RM Length L Ch R = 1 ,449.35  ,5321.588,5321.588,5321.588
BEGIN DESCRIPTION:
ROK7
END DESCRIPTION:
Node Name=ROK7
XS GIS Cut Line= 2
 451531.470204883181508.48117002 451753.720604883181451.33097002
#Sta/Elev= 30
    1969    28.9    1997    28.9    2000    28.4    2006    23.8    2015    23.1
    2016    20.2    2020    20.1    2025    20.5    2035    22.9    2050    22.9
    2055    23.6    2060    23.1    2085    23.9    2115    22.9    2125    23.5
    2135    23.5    2138   23.75    2143    25.1    2171    23.8    2173    23.3
    2177    23.2    2183    23.8    2185    24.9    2200    24.4    2300    23.9
    2400    24.9    2500    24.8    2600    25.3    2650      24    3000    28.9
#Mann= 3 , 0 , 0
    1969     .15       0    2006     .13       0    2085     .15       0
Bank Sta=2006,2085
XS Rating Curve= 0 ,0
Exp/Cntr=0.3,0.1

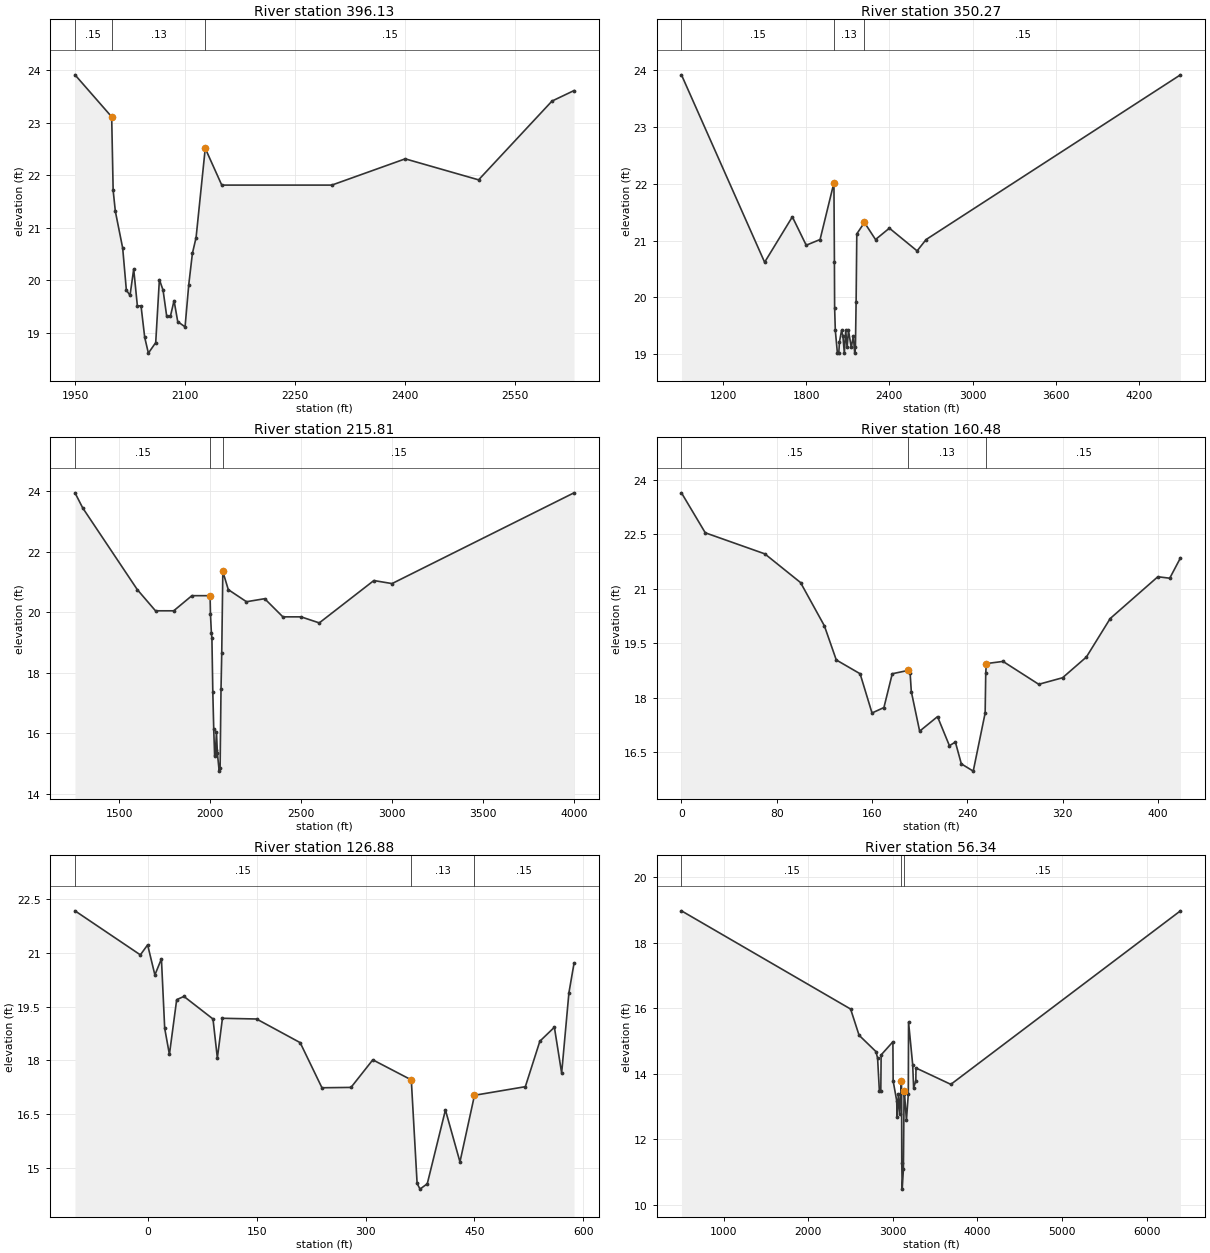
Type RM Length L Ch R = 1 ,396.13  ,4586.122,4586.122,4586.122
BEGIN DESCRIPTION:
ROK6
END DESCRIPTION:
Node Name=ROK6
XS GIS Cut Line= 2
450737.7186048793182638.78337002451099.6693048793182740.38357002
#Sta/Elev= 30
    1950   23.91    2000   23.11    2002   21.71    2005   21.31    2015   20.61
    2020   19.81    2025   19.71    2030   20.21    2035   19.51    2040   19.51
    2045   18.91    2050   18.61    2060   18.81    2065   20.01    2070   19.81
    2075   19.31    2080   19.31    2085   19.61    2090   19.21    2100   19.11
    2105   19.91    2110   20.51    2115   20.81  2127.5   22.51    2150   21.81
    2300   21.81    2400   22.31    2500   21.91    2600   23.41    2630   23.61
#Mann= 3 , 0 , 0
    1950     .15       0    2000     .13       0  2127.5     .15       0
Bank Sta=2000,2127.5
XS Rating Curve= 0 ,0
Exp/Cntr=0.3,0.1

Type RM Length L Ch R = 1 ,350.27  ,13446.29,13446.29,13446.29
BEGIN DESCRIPTION:
ROK5
END DESCRIPTION:
Node Name=ROK5
XS GIS Cut Line= 2
 451861.670804883183629.38537002 451766.420704883183273.78467002
#Sta/Elev= 30
     900   23.92    1500   20.62    1700   21.42    1800   20.92    1900   21.02
    2000   22.02  2003.5   20.63    2005   19.82    2010   19.42    2025   19.02
    2035   19.02    2040   19.22    2055   19.42    2065   19.32    2075   19.02
    2085   19.42    2095   19.12    2105   19.42    2125   19.12    2140   19.32
    2150   19.02    2155   19.12    2160   19.92    2165   21.12    2220   21.32
    2300   21.02    2400   21.22    2600   20.82    2665   21.02    4500   23.92
#Mann= 3 , 0 , 0
     900     .15       0    2000     .13       0    2220     .15       0
Bank Sta=2000,2220
XS Rating Curve= 0 ,0
Exp/Cntr=0.3,0.1

Type RM Length L Ch R = 1 ,215.81  ,5532.677,5532.677,5532.677
BEGIN DESCRIPTION:
ROK4
END DESCRIPTION:
Node Name=ROK4
XS GIS Cut Line= 2
 453798.424704883181095.73027002453442.8240048793181038.58017002
#Sta/Elev= 30
  1257.5   23.94    1300   23.44    1600   20.74    1700   20.04    1800   20.04
    1900   20.54    2000   20.54    2002   19.94    2007   19.32    2010   19.14
    2015   17.34    2020   16.14    2025   15.24    2030   15.44    2035   16.04
    2040   15.34    2050   14.74    2055   14.84    2060   17.44    2064   18.64
    2070   21.34    2100   20.74    2200   20.34    2300   20.44    2400   19.84
    2500   19.84    2600   19.64    2900   21.04    3000   20.94    4000   23.94
#Mann= 3 , 0 , 0
  1257.5     .15       0    2000     .13       0    2070     .15       0
Bank Sta=2000,2070
XS Rating Curve= 0 ,0
Exp/Cntr=0.3,0.1

Type RM Length L Ch R = 1 ,160.48  ,3360.203,3360.203,3360.203
BEGIN DESCRIPTION:
ROK3
END DESCRIPTION:
Node Name=ROK3
XS GIS Cut Line= 2
 453683.837304883179720.61477002 453618.766804883179618.24147002
#Sta/Elev= 30
       0  23.645      20  22.545      70  21.965     100  21.175     120  19.985
     130  19.045     150  18.665     160  17.585     170  17.735     177  18.665
     190  18.755     192  18.685     193  18.175     200  17.085     215  17.485
     225  16.685     230  16.785     235  16.185     245  15.985     255  17.585
   255.5  18.685     256  18.945     270  19.005     300  18.375     320  18.555
     340  19.125     360  20.185     400  21.335     410  21.295     419  21.855
#Mann= 3 , 0 , 0
       0     .15       0     190     .13       0     256     .15       0
Bank Sta=190,256
XS Rating Curve= 0 ,0
Exp/Cntr=0.3,0.1

Type RM Length L Ch R = 1 ,126.88  ,7053.478,7053.478,7053.478
BEGIN DESCRIPTION:
ROK2
END DESCRIPTION:
Node Name=ROK2
XS GIS Cut Line= 2
454544.9803048793179351.14227002 454484.226104883179114.52637002
#Sta/Elev= 30
    -100  22.173     -10  20.943       0  21.223      10  20.383      19  20.833
    23.5  18.893      30  18.163      40  19.693      50  19.783      90  19.153
      96  18.063     103  19.173     150  19.153     210  18.493     240  17.233
     280  17.243     310  18.013     363  17.453     371  14.563     375  14.403
     385  14.553     410  16.613     430  15.163     450  17.023     520  17.263
     540  18.533     560  18.923     570  17.643     580  19.883     587  20.703
#Mann= 3 , 0 , 0
    -100     .15       0     363     .13       0     450     .15       0
Bank Sta=363,450
XS Rating Curve= 0 ,0
Exp/Cntr=0.3,0.1

Type RM Length L Ch R = 1 ,56.34   ,3817.881,3817.881,3817.881
BEGIN DESCRIPTION:
ROK1
END DESCRIPTION:
Node Name=ROK1
XS GIS Cut Line= 2
455779.6287048793178130.27437002455392.2779048793178035.02417002
#Sta/Elev= 30
     500   18.97    2500   15.97    2600   15.17    2800   14.67    2819   14.47
    2840   13.47    2857   13.47    2861   14.57    3000   14.97    3003   13.77
    3045   13.17    3050   12.67    3065   13.37    3080   12.77    3100   13.77
    3103   13.47    3105   11.27    3110   10.47    3124   11.07    3132   13.37
    3135   13.47    3160   12.57    3182   13.37    3185   15.57    3234   14.27
    3245   13.57    3271   13.77    3273   14.17    3685   13.67    6400   18.97
#Mann= 3 , 0 , 0
     500     .15       0    3100     .13       0    3135     .15       0
Bank Sta=3100,3135
XS Rating Curve= 0 ,0
Exp/Cntr=0.3,0.1

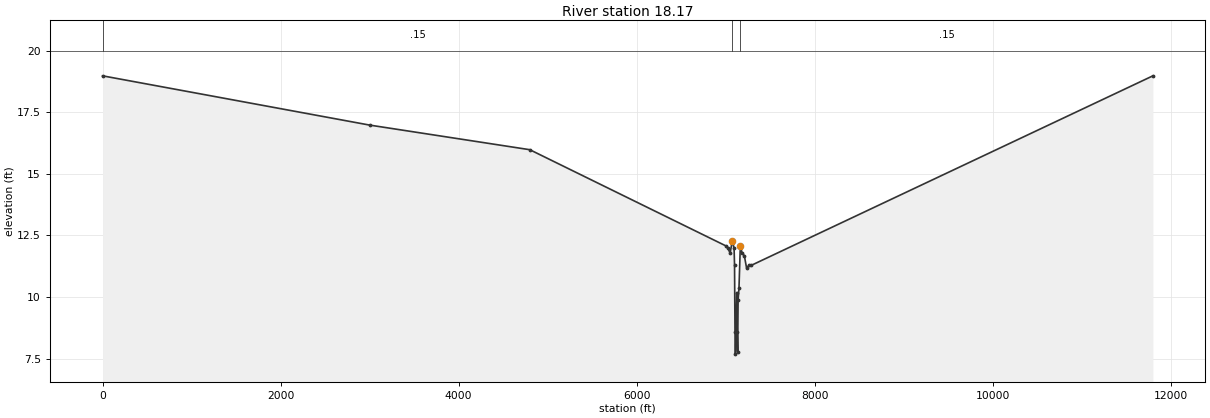
Type RM Length L Ch R = 1 ,18.17   ,1816.503,1816.503,1816.503
BEGIN DESCRIPTION:
WK16
END DESCRIPTION:
Node Name=WK16
XS GIS Cut Line= 2
 456154.279404883176999.97207002455735.1786048793176961.87207002
#Sta/Elev= 23
       0   18.98    3000   16.98    4800   15.98    7000   12.08    7025   11.98
    7050   11.78    7075   12.28    7095   11.98    7100   11.28    7105    8.58
    7110    7.68    7125   10.18    7130    8.58    7135    7.78    7140    9.88
    7150   10.38    7165   12.08    7185   11.78    7210   11.68    7235   11.18
    7260   11.28    7285   11.28   11800   18.98
#Mann= 3 , 0 , 0
       0     .15       0    7075     .13       0    7165     .15       0
Bank Sta=7075,7165
XS Rating Curve= 0 ,0
Exp/Cntr=0.3,0.1

River Reach=wekiva          ,wek_run

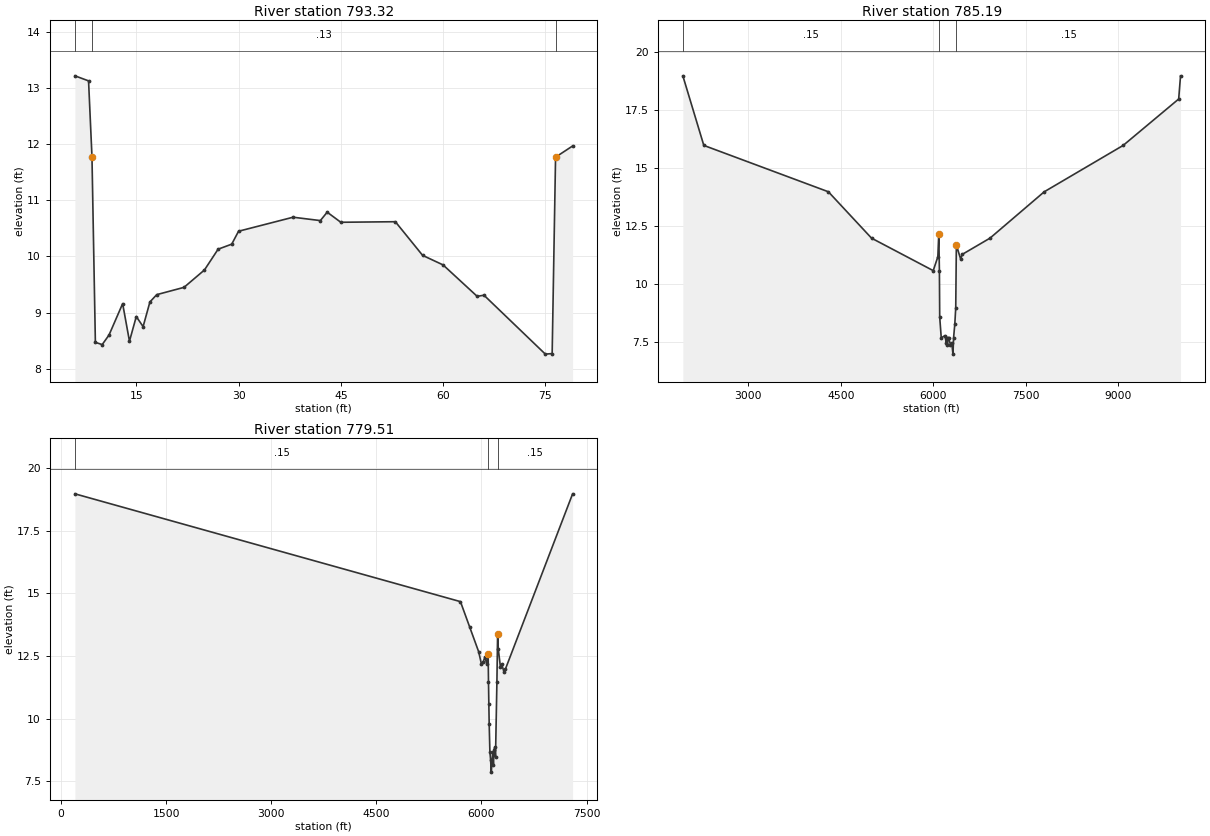
Type RM Length L Ch R = 1 ,793.32  ,813.0906,813.0906,813.0906
BEGIN DESCRIPTION:
WekSpr6
WekSpr6
END DESCRIPTION:
Node Name=WekSpr6
XS GIS Cut Line= 2
     455071.1753     3176243.645     455098.0644     3176211.408
#Sta/Elev= 30
       6   13.22       8   13.13     8.5   11.78       9    8.47      10    8.43
      11     8.6      13    9.16      14    8.49      15    8.93      16    8.75
      17    9.19      18    9.32      22    9.45      25    9.76      27   10.13
      29   10.22      30   10.45      38    10.7      42   10.64      43   10.79
      45   10.61      53   10.62      57   10.02      60    9.85      65    9.29
      66    9.31      75    8.26      76    8.27    76.5   11.77      79   11.97
#Mann= 3 , 0 , 0
       6     .15       0     8.5     .13       0    76.5     .15       0
Bank Sta=8.5,76.5
XS Rating Curve= 0 ,0
Exp/Cntr=0.3,0.1

Type RM Length L Ch R = 1 ,785.19  ,567.8806,567.8806,567.8806
BEGIN DESCRIPTION:
WEK13
END DESCRIPTION:
Node Name=WEK13
XS GIS Cut Line= 2
 455163.677404883176530.07117002455328.7778048793176295.12067002
#Sta/Elev= 30
    1940   18.99    2280   15.99    4300   13.99    5000   11.99    6000   10.59
    6075   11.19    6090   12.19    6100   10.59    6105    8.59    6130    7.69
    6190    7.79    6210    7.49    6220    7.69    6230    7.39    6240    7.69
    6250    7.69    6280    7.39    6300    7.49    6320    6.99    6330    7.69
    6350    8.29    6365    8.99    6375   11.69    6445   11.09    6470   11.29
    6920   11.99    7800   13.99    9080   15.99    9980   17.99   10010   18.99
#Mann= 3 , 0 , 0
    1940     .15       0    6090     .13       0    6375     .15       0
Bank Sta=6090,6375
XS Rating Curve= 0 ,0
Exp/Cntr=0.3,0.1

Type RM Length L Ch R = 1 ,779.51  ,3231.857,3231.857,3231.857
BEGIN DESCRIPTION:
WK17
END DESCRIPTION:
Node Name=WK17
XS GIS Cut Line= 2
      455414.687     3176429.959      455415.957     3176385.507
#Sta/Elev= 28
     200   18.97    5700   14.67    5830   13.67    5960   12.67    6000   12.17
    6025   12.27    6050   12.47    6075   12.17    6095   12.57    6100   11.47
    6105   10.57    6110    9.77    6120    8.67    6130    8.37    6140    7.87
    6160    8.67    6170    8.17    6180    8.77    6190    8.87    6200    8.47
    6220   11.47    6230   13.37    6240   12.77    6270   12.07    6290   12.17
    6320   11.87    6340   11.97    7300   18.97
#Mann= 3 , 0 , 0
     200     .15       0    6095     .13       0    6230     .15       0
Bank Sta=6095,6230
XS Rating Curve= 0 ,0
Exp/Cntr=0.3,0.1

River Reach=wekiva          ,wekiva_riv_up